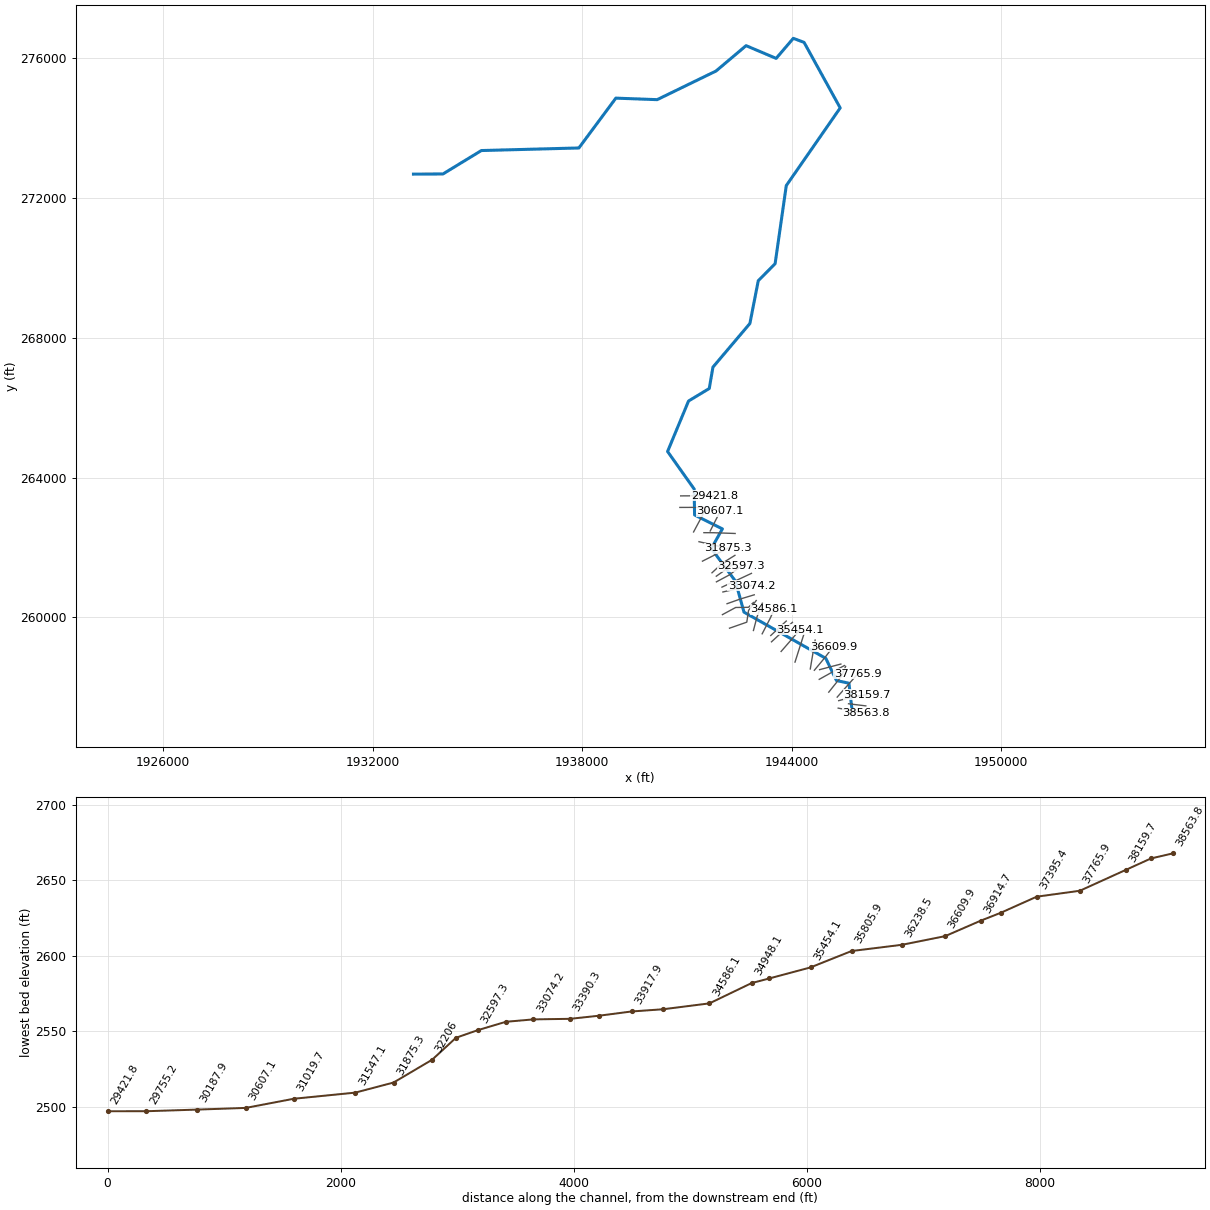
--- LttlBvrCrk.prj (project) ---

Proj Title=LttlBvrCrk
Current Plan=p01
Default Exp/Contr=0,0
English Units
Geom File=g01
Flow File=f01
Plan File=p01
BEGIN DESCRIPTION:
END DESCRIPTION:
DSS Export Rating Curves= 0
DSS Export Rating Curve Sorted= 0
DSS Export Volume Flow Curves= 0
DXF OffsetX= 0
DXF OffsetY= 0
DXF ScaleX= 0
DXF ScaleY= 0

--- LttlBvrCrk.p01 (plan) ---

Plan Title=Floodplain
Program Version=4.00
Geom File=g01
Flow File=f01
K Sum by GR=0
Std Step Tol=0.01
Critical Tol=0.01
Num of Std Step Trials=20
Max Error Tol=0.3
Flow Tol Ratio=0.001
Split Flow NTrial=30
Split Flow Tol=0.02
Split Flow Ratio=0.02
Log Output Level=0
Friction Slope Method=1
Unsteady Friction Slope Method=2
Unsteady Bridges Friction Slope Method=1
Global Log Level=0
CheckData=False
Run HTab=0
Run UNet=0
Run PostProcess=0
UNET Theta=0
UNET Theta Warmup=0
UNET ZTol=0
UNET ZSATol=0
UNET MxIter=0
UNET MaxInSteps=0
UNET DtIC=0
UNET DtMin=0
UNET MaxCRTS=0
UNET WFStab=0
UNET SFStab=0
UNET WFX=0
UNET SFX=0
UNET DSS MLevel=0
UNET DZMax Abort=0
UNET Convert EG Bridges=0
UNET Use Existing IB Tables=0
UNET Froude Limit=0
UNET Froude Power=0
Write IC File=0
Echo Input=False
Echo Output=False
Write Detailed=0

--- LttlBvrCrk.f01 (steady flow) ---

Flow Title=NFF Regression Equation
Program Version=4.00
Number of Profiles=1
Profile Names=P100yr
River Rch & RM=LttlBvrCrk,Main      ,38563.8
598.3089
River Rch & RM=LttlBvrCrk,Main      ,37765.9
641.7967
River Rch & RM=LttlBvrCrk,Main      ,35805.9
696.1052
River Rch & RM=LttlBvrCrk,Main      ,33917.9
768.1668
River Rch & RM=LttlBvrCrk,Main      ,33390.3
840.4063
River Rch & RM=LttlBvrCrk,Main      ,31019.7
887.7087
River Rch & RM=LttlBvrCrk,Main      ,28180.6
982.2552
River Rch & RM=LttlBvrCrk,Main      ,27758.8
1098.627
River Rch & RM=LttlBvrCrk,Main      ,23035.6
1196.921
River Rch & RM=LttlBvrCrk,Main      ,22829.8
1411.972
River Rch & RM=LttlBvrCrk,Main      ,15819.9
1517.209
River Rch & RM=LttlBvrCrk,Main      ,15579.2
1723.996
River Rch & RM=LttlBvrCrk,Main      ,11905.3
1834.863
River Rch & RM=LttlBvrCrk,Main      ,4831.1
2038.580
River Rch & RM=LttlBvrCrk,Main      ,1833.2
2260.238
River Rch & RM=LttlBvrCrk,Main      ,143.2
2451.380
Boundary for River Rch & Prof#=LttlBvrCrk,Main      ,1
Up Type=0
Dn Type=3
Dn Slope=0.020668

--- LttlBvrCrk.g01 (geometry) ---

Geom Title=USGS 3m DEM
Program Version=4.10

River Reach=LttlBvrCrk      ,Main
Reach XY= 30
     1945736.223      257316.707     1945643.529      258114.596
     1945287.037      258190.403     1944981.047       258825.82
     1942637.297      260148.736     1942389.449      261040.179
      1941701.87      261968.973     1942018.808      262531.549
     1941222.294      262929.809     1941210.214      263672.174
     1940448.495      264746.392     1941050.058      266191.705
     1941642.883      266549.091     1941747.974      267160.455
     1942806.448      268409.182     1943046.152      269633.111
     1943529.224      270121.392     1943849.537       272357.07
     1945393.365      274579.223     1944358.652      276454.726
     1944050.058      276570.611       1943559.1       275996.79
     1942697.193      276360.976     1941837.082       275635.12
     1940149.849      274815.723     1938967.389      274859.166
     1937908.033      273433.163     1935115.015      273359.302
     1934015.002       272689.09     1933169.827      272684.807

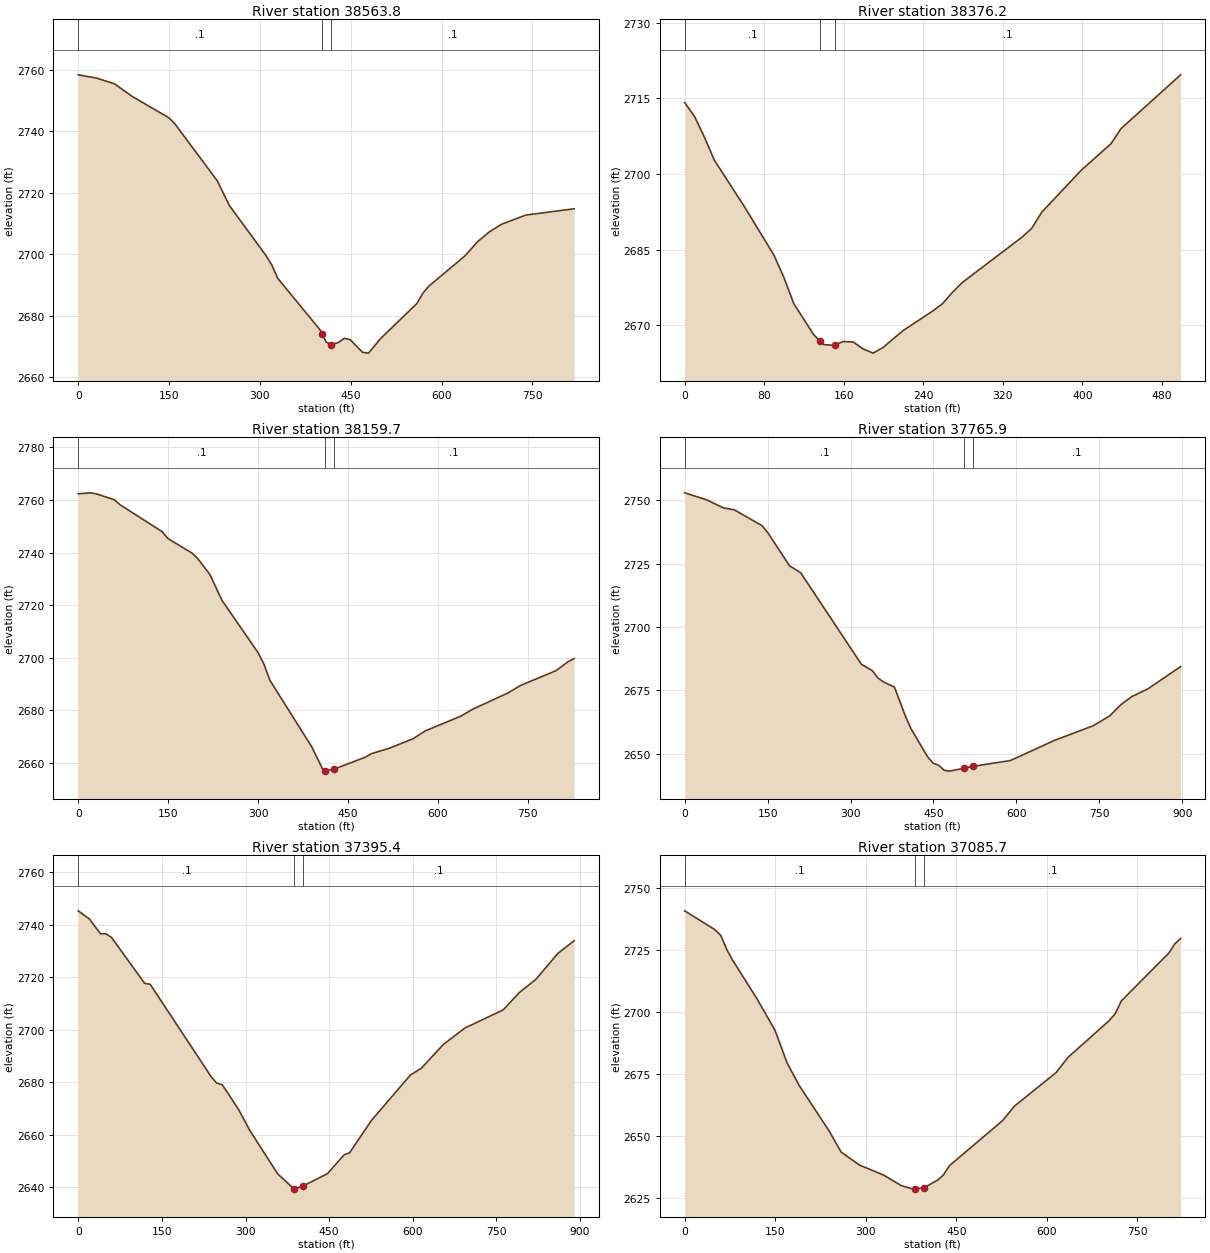
Type RM Length L Ch R = 1 ,38563.8 ,185.7,187.1,188.6
XS GIS Cut Line= 3
     1945335.489      257401.573     1945738.056      257326.537
     1946140.622      257251.502
#Sta/Elev= 30
       0 2758.44      30 2757.39    59.9 2755.52    89.9 2751.31   149.8 2744.46
   159.8 2742.45   229.7 2723.94   249.7 2715.88   309.6 2699.74   319.6 2696.58
   329.6 2692.17   399.5 2675.42   402.9 2674.07   409.5 2671.44   417.9 2670.63
   429.5  2671.3   439.5 2672.68   449.4 2672.21   469.4 2668.13   479.4 2667.85
   499.4 2672.61   559.3    2684   569.3 2687.39   579.3 2689.69   639.2  2699.6
   659.2 2704.08   679.2 2707.35   699.2 2709.81   739.1 2712.78     819 2714.84
#Mann= 3 , 0 , 0
       0      .1       0   402.9    .045       0   417.9      .1       0
Bank Sta=402.9,417.9
XS Rating Curve= 0 ,0
Exp/Cntr=0.3,0.1

Type RM Length L Ch R = 1 ,38376.2 ,207.6,216.2,222.4
XS GIS Cut Line= 2
     1945632.044      257526.175     1946127.271      257466.085
#Sta/Elev= 30
       0 2714.18      10 2711.37      20 2707.23    29.9 2702.73    59.9 2693.58
    89.8 2683.92    99.8 2679.51   109.8 2674.29   129.7 2668.17   136.5 2666.83
   139.7  2666.2   149.7 2666.04   151.5 2666.18   159.6  2666.8   169.6  2666.7
   179.6 2665.32   189.6  2664.5   199.5 2665.61   219.5 2668.94   249.4 2672.83
   259.4  2674.3   269.4 2676.55   279.4 2678.51   339.2 2687.46   349.2 2689.24
   359.2 2692.43   399.1 2700.77     429 2706.03     439    2709   498.9 2719.65
#Mann= 3 , 0 , 0
       0      .1       0   136.5    .045       0   151.5      .1       0
Bank Sta=136.5,151.5
XS Rating Curve= 0 ,0
Exp/Cntr=0.3,0.1

Type RM Length L Ch R = 1 ,38159.7 ,379.5,393.9,410.7
XS GIS Cut Line= 3
     1945350.686       257615.74     1945755.911      257723.986
     1946158.924      257785.937
#Sta/Elev= 30
       0 2762.38      20 2762.75      30 2762.38    59.9 2760.15    69.9  2758.2
   139.8 2748.02   149.8 2745.35   189.7 2739.85   199.7 2737.66   219.7 2731.68
   239.7 2721.91   299.6 2702.11   309.6 2697.72   319.6 2691.51   389.5 2666.17
   409.4 2656.92   411.9 2656.93   426.9  2657.7   479.1 2662.23     489 2663.55
   518.9 2665.62   558.7 2669.25   578.6 2672.19   638.2 2677.82   658.1 2680.48
   717.8 2686.75   737.7 2689.49   797.4 2695.18   817.2 2698.55   827.2 2699.71
#Mann= 3 , 0 , 0
       0      .1       0   411.9    .045       0   426.9      .1       0
Bank Sta=411.9,426.9
XS Rating Curve= 0 ,0
Exp/Cntr=0.3,0.1

Type RM Length L Ch R = 1 ,37765.9 ,370,370.2,370.3
XS GIS Cut Line= 3
      1945306.83      257716.914     1945829.582      258307.866
      1945897.27      258392.131
#Sta/Elev= 30
       0 2752.92      40 2750.14    69.9    2747    89.9  2746.2   139.8 2739.98
   149.8 2737.39   189.8 2724.09   209.7 2721.43   319.6  2685.3   339.6 2682.74
   349.6 2679.88   359.5 2678.32   379.5 2676.28   399.5  2664.7   409.5 2659.83
   439.4 2648.78   449.4 2646.27   459.4 2645.45   469.4 2643.46   479.4 2643.12
   505.9 2644.29   520.9    2645   589.2  2647.3   669.1 2655.26     739 2661.03
     769 2664.94     789 2669.32   808.6 2672.49   838.1 2675.61   897.1 2684.36
#Mann= 3 , 0 , 0
       0      .1       0   505.9    .045       0   520.9      .1       0
Bank Sta=505.9,520.9
XS Rating Curve= 0 ,0
Exp/Cntr=0.3,0.1

Type RM Length L Ch R = 1 ,37395.4 ,318.3,309.7,301
XS GIS Cut Line= 3
     1945065.845      257858.378     1945431.743      258316.155
     1945547.985      258596.275
#Sta/Elev= 30
       0 2745.21    19.9 2742.14    39.7  2736.5    49.7 2736.46    59.6  2735.1
   119.2 2717.58   129.1 2717.22   238.4 2682.03   248.3  2679.6   258.2 2678.97
   268.2 2675.83     288 2669.36   307.9  2661.5   357.6 2645.04   387.4  2639.2
   387.6 2639.21   402.6 2640.35     447 2645.09   476.8 2652.27   486.7 2653.05
   526.4 2665.53   595.8 2682.68   615.4 2685.27   654.5 2694.26   693.6 2700.59
   762.1 2707.49   791.5 2714.18   820.8 2719.14     860 2728.97   889.3 2733.83
#Mann= 3 , 0 , 0
       0      .1       0   387.6    .045       0   402.6      .1       0
Bank Sta=387.6,402.6
XS Rating Curve= 0 ,0
Exp/Cntr=0.3,0.1

Type RM Length L Ch R = 1 ,37085.7 ,176.3,170.6,165
XS GIS Cut Line= 3
     1944792.962      258225.668     1945150.206      258424.732
     1945513.599       258620.04
#Sta/Elev= 30
       0 2740.64    49.9 2733.07    59.8 2730.75    69.8 2725.02    79.8 2720.59
   119.7 2705.24   149.6 2692.52   169.6 2679.39   189.5 2670.35   239.4 2651.88
   259.3 2643.41   289.3 2638.23   329.2  2634.2   359.1 2629.89     379  2628.5
   382.1 2628.53   397.1 2629.15   418.8 2632.11   428.6  2634.2   438.4 2637.91
   526.8 2656.15   546.5    2662   615.2 2675.45   634.9 2681.58   703.6 2696.49
   713.5 2699.34   723.3 2704.34   801.9  2723.6   811.7 2727.29   821.5 2729.52
#Mann= 3 , 0 , 0
       0      .1       0   382.1    .045       0   397.1      .1       0
Bank Sta=382.1,397.1
XS Rating Curve= 0 ,0
Exp/Cntr=0.3,0.1

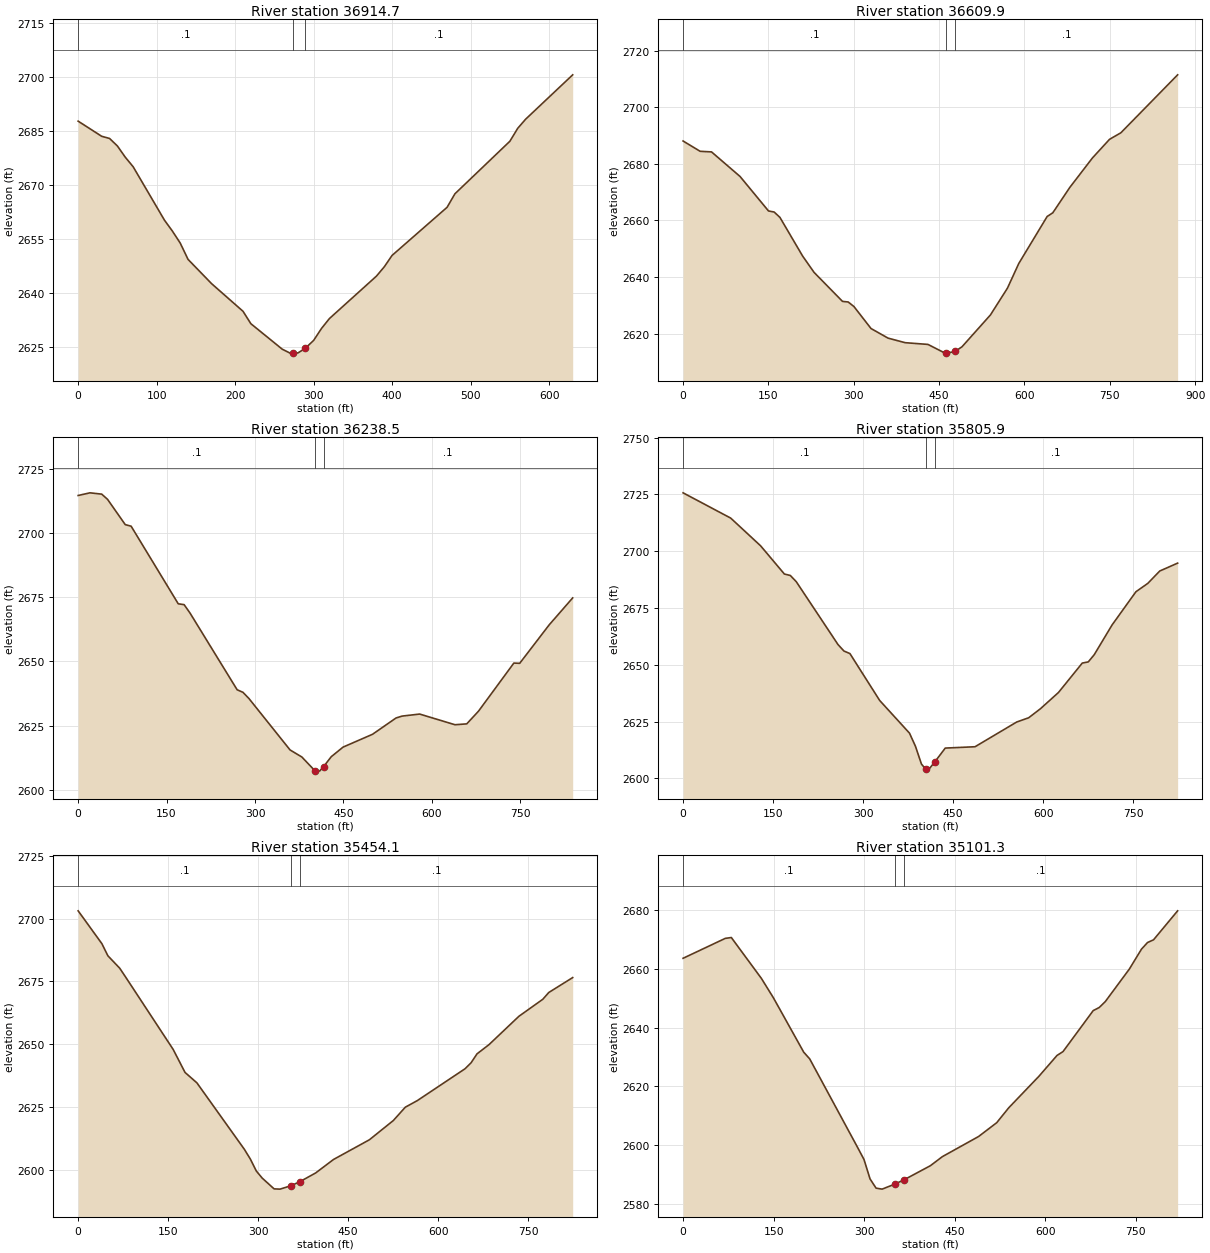
Type RM Length L Ch R = 1 ,36914.7 ,290.7,304.8,319.9
XS GIS Cut Line= 2
     1944803.213      258502.642     1945412.404      258662.882
#Sta/Elev= 30
       0 2687.82      30 2683.61      40 2683.01      50 2680.92      60 2677.81
      70 2675.16     110 2660.27     120 2657.27     130 2653.93     140 2649.38
     170 2642.63     210 2634.95     220  2631.5     260 2624.41     270 2623.32
   274.1 2623.34     280 2623.38   289.1 2624.62     300 2626.87     310 2630.19
     320 2632.92     380 2644.74     390 2647.34   399.9  2650.5   469.9 2663.86
   479.9 2667.62   549.9 2682.23   559.9 2685.83   569.9 2688.35   629.9  2700.7
#Mann= 3 , 0 , 0
       0      .1       0   274.1    .045       0   289.1      .1       0
Bank Sta=274.1,289.1
XS Rating Curve= 0 ,0
Exp/Cntr=0.3,0.1

Type RM Length L Ch R = 1 ,36609.9 ,359.2,371.2,382.2
XS GIS Cut Line= 3
     1944652.635      258485.217     1944953.727      258846.635
     1945195.387      259163.816
#Sta/Elev= 30
       0 2688.09      30 2684.44      50 2684.23   100.1 2675.55   150.1 2663.36
   160.1 2662.97   170.2 2661.08   210.2 2647.38   230.2 2641.64   280.2 2631.38
   290.2 2631.17   300.3 2629.56   330.3 2621.79   360.3 2618.39   390.3 2616.78
   430.4 2616.17   460.4 2613.09   462.9 2613.09   477.9 2613.67   490.3 2615.35
   540.2 2626.59   570.1 2636.06     590 2644.77   639.9  2661.4   649.8  2662.7
   679.8  2671.7   719.6 2682.12   749.5 2688.67   769.5    2691   869.2 2711.48
#Mann= 3 , 0 , 0
       0      .1       0   462.9    .045       0   477.9      .1       0
Bank Sta=462.9,477.9
XS Rating Curve= 0 ,0
Exp/Cntr=0.3,0.1

Type RM Length L Ch R = 1 ,36238.5 ,435.9,432.6,429.4
XS GIS Cut Line= 2
     1944536.197      258522.764     1944675.593      259350.036
#Sta/Elev= 30
       0 2714.54      20 2715.58      40 2715.07    49.9 2713.04    79.9 2703.22
    89.9  2702.6   169.8 2672.43   179.8 2672.09   189.8 2668.82   269.7    2639
   279.6    2638   289.6 2635.63   359.5 2615.59   379.5 2612.85   401.5 2607.54
   409.5 2607.36   416.5 2609.15   429.4 2612.98   449.4  2616.7   499.4 2621.69
   539.3 2628.03   549.3 2628.75   579.3 2629.55   639.2  2625.4   659.2 2625.74
   679.1 2630.66   739.1 2649.38     749 2649.28     799 2664.23   838.9 2674.72
#Mann= 3 , 0 , 0
       0      .1       0   401.5    .045       0   416.5      .1       0
Bank Sta=401.5,416.5
XS Rating Curve= 0 ,0
Exp/Cntr=0.3,0.1

Type RM Length L Ch R = 1 ,35805.9 ,361,351.6,342.1
XS GIS Cut Line= 2
     1944098.669      258718.607     1944349.391       259503.62
#Sta/Elev= 30
       0 2725.69    79.4 2714.56   129.1  2702.4   168.8 2689.96   178.7 2689.32
   188.6 2686.59   258.2 2658.91   268.1 2656.06     278 2654.96   327.6 2634.32
   377.3 2619.93   387.2 2614.18   397.2 2606.34   404.2 2604.13   407.1 2603.22
   419.2 2607.19   436.9 2613.36   486.5 2613.95     556 2624.84   575.9  2626.7
   595.7 2630.72   625.5 2637.81   665.2 2650.77   675.2 2651.29   685.1 2654.44
   714.9 2667.56   754.6 2682.16   774.4 2685.84   794.3 2691.28   824.1 2694.75
#Mann= 3 , 0 , 0
       0      .1       0   404.2    .045       0   419.2      .1       0
Bank Sta=404.2,419.2
XS Rating Curve= 0 ,0
Exp/Cntr=0.3,0.1

Type RM Length L Ch R = 1 ,35454.1 ,354.8,352.4,349.9
XS GIS Cut Line= 3
     1943701.073      259023.864     1943974.223      259337.065
     1944238.748      259648.255
#Sta/Elev= 30
       0 2703.07    39.6 2689.99    49.5 2685.21    69.3 2680.24    79.2  2676.7
   158.3 2647.96   178.1  2638.8   197.9 2634.65     277 2608.21     287 2604.32
   296.8 2599.62   306.7 2596.77   326.5 2592.49   336.4 2592.39   354.9 2593.76
   369.9 2595.41   395.8 2598.83   425.5 2604.18   485.3 2612.02   525.2 2619.68
   545.1 2624.97     565 2627.58   644.7 2640.27   654.7 2642.64   664.6 2646.19
   684.5 2649.84   734.4 2661.13   774.2 2667.89   784.2  2670.6     824 2676.52
#Mann= 3 , 0 , 0
       0      .1       0   354.9    .045       0   369.9      .1       0
Bank Sta=354.9,369.9
XS Rating Curve= 0 ,0
Exp/Cntr=0.3,0.1

Type RM Length L Ch R = 1 ,35101.3 ,153,153.1,153.2
XS GIS Cut Line= 3
     1943425.626      259299.178     1943726.304      259577.172
     1944024.726      259857.614
#Sta/Elev= 30
       0 2663.54    69.9  2670.3    79.9 2670.59   129.8 2656.67   149.8 2650.04
   199.8 2631.64   209.7 2629.36   289.6 2599.05   299.6 2595.18   309.6  2588.6
   319.6 2585.44   329.6 2585.11   351.4 2586.87   366.4 2588.33   409.5 2593.06
   429.5 2596.16   489.4 2602.99   519.4 2607.68   539.3 2612.74   589.3 2623.45
   619.2 2630.51   629.2 2631.84   679.2 2645.76   689.2 2646.82   699.2 2648.82
   739.1 2659.89   759.1 2666.63   769.1 2668.88   779.1 2669.81     819 2679.66
#Mann= 3 , 0 , 0
       0      .1       0   351.4    .045       0   366.4      .1       0
Bank Sta=351.4,366.4
XS Rating Curve= 0 ,0
Exp/Cntr=0.3,0.1

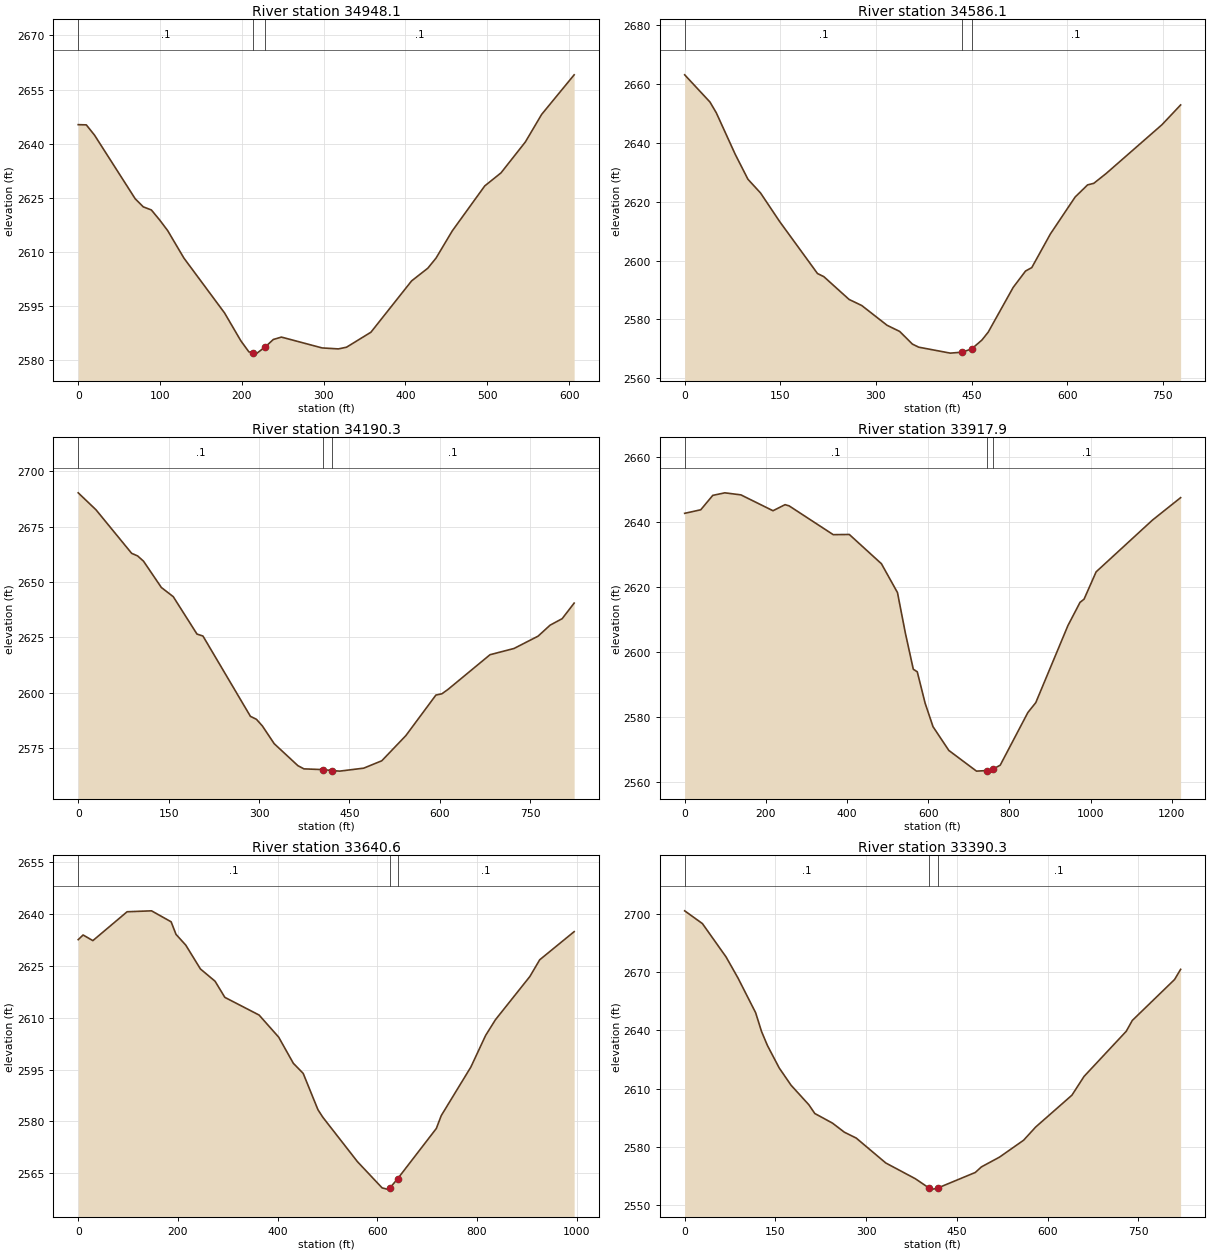
Type RM Length L Ch R = 1 ,34948.1 ,354,361.9,369.7
XS GIS Cut Line= 2
     1943404.505      259479.916     1943847.478       259893.78
#Sta/Elev= 30
       0 2645.29     9.9 2645.23    19.9  2642.4    69.6 2624.79    79.5 2622.53
    89.4 2621.67    99.4 2618.94   109.3 2615.97   129.2 2608.34   178.9 2593.14
   198.8 2585.43   208.7 2582.35   213.7 2582.18   218.6 2582.02   228.7 2583.76
   238.5  2585.8   248.4 2586.46   298.1 2583.46     318 2583.19     328 2583.66
   357.8 2587.81   407.5 2602.02   427.3 2605.53   437.3 2608.31   457.2 2615.86
   496.9 2628.32   516.8 2631.94   546.6 2640.51   566.5 2648.14   606.2 2659.09
#Mann= 3 , 0 , 0
       0      .1       0   213.7    .045       0   228.7      .1       0
Bank Sta=213.7,228.7
XS Rating Curve= 0 ,0
Exp/Cntr=0.3,0.1

Type RM Length L Ch R = 1 ,34586.1 ,391,395.4,397
XS GIS Cut Line= 3
     1943158.256       259528.44     1943381.768      259960.003
      1943503.33      260225.229
#Sta/Elev= 30
       0 2663.02    39.7 2653.78    49.6 2650.13    79.4 2635.99    99.2 2627.59
     119 2622.92   148.8 2613.28   208.3 2595.59   218.2 2594.54   257.9 2586.79
   277.7 2584.74   317.4 2578.03   337.2 2575.94   357.1 2571.65     367  2570.6
   416.6 2568.58     435  2568.9     450 2569.99   466.2 2573.02   476.1 2575.72
   515.2 2590.88   534.6 2596.44   544.4 2597.61   573.5    2609   612.4 2621.56
   631.9 2625.67   641.6  2626.2   661.1 2629.55   748.6  2646.1   777.8  2652.8
#Mann= 3 , 0 , 0
       0      .1       0     435    .045       0     450      .1       0
Bank Sta=435,450
XS Rating Curve= 0 ,0
Exp/Cntr=0.3,0.1

Type RM Length L Ch R = 1 ,34190.3 ,270,272.3,277.4
XS GIS Cut Line= 3
     1942907.953      259622.945     1943013.551      260023.236
     1943163.118      260403.957
#Sta/Elev= 30
       0 2690.24    29.6 2682.56    88.7 2662.94    98.6 2661.78   108.4  2659.4
     138 2647.54   157.7 2643.41   197.1 2626.53     207 2625.65   285.8 2589.42
   295.7  2588.1   305.6 2585.09   325.3 2577.07   364.7 2567.14   374.6 2565.73
   406.5 2565.39   421.5 2564.96   433.9 2564.71   473.8 2566.05   503.8 2569.38
   543.7 2580.72   593.6 2599.02   603.5 2599.59   613.5 2601.53   683.4 2617.22
   723.3 2620.04   763.2  2625.6   783.1 2630.55   803.1 2633.47     823  2640.5
#Mann= 3 , 0 , 0
       0      .1       0   406.5    .045       0   421.5      .1       0
Bank Sta=406.5,421.5
XS Rating Curve= 0 ,0
Exp/Cntr=0.3,0.1

Type RM Length L Ch R = 1 ,33917.9 ,309.4,277.4,245.4
XS GIS Cut Line= 4
     1942222.786      259689.251     1942717.815      259862.058
     1942768.433      260198.982     1942987.649      260480.568
#Sta/Elev= 30
       0 2642.71    39.6  2643.8    69.2 2648.24    98.9 2649.03   138.5  2648.4
   217.6 2643.51   247.3 2645.38   257.2 2645.02     366 2636.13   405.6 2636.19
   484.8 2627.16   524.3 2618.27   543.8 2605.74   563.3 2594.63     573 2593.86
   592.5 2584.14   611.9 2576.92   650.9 2569.59     719 2563.22   743.9 2563.39
   758.9 2563.81   777.4 2565.05   845.6  2581.3     865 2584.33   944.3 2608.11
   974.1 2615.26     984 2616.24  1013.7 2624.66  1152.5 2640.62  1221.9 2647.54
#Mann= 3 , 0 , 0
       0      .1       0   743.9    .045       0   758.9      .1       0
Bank Sta=743.9,758.9
XS Rating Curve= 0 ,0
Exp/Cntr=0.3,0.1

Type RM Length L Ch R = 1 ,33640.6 ,242.8,250.1,256.5
XS GIS Cut Line= 4
     1942019.722      260077.421     1942399.618      260282.187
      1942765.67      260287.391     1942907.953      260424.148
#Sta/Elev= 30
       0 2632.53     9.8 2633.88    29.4 2632.25    98.1 2640.59   147.1 2640.86
   186.4 2637.69   196.2 2634.06   215.8 2630.95   245.2 2624.06   274.6 2620.51
   294.2 2615.85   362.9 2610.74   402.1 2604.37   431.6  2596.8   451.4 2593.87
     481 2583.38   490.9 2581.18   560.2 2568.37   609.7 2560.79   619.6 2560.43
   625.9 2560.86   640.9 2563.44   718.5 2577.96   728.4 2581.69   787.8 2595.72
   817.4 2604.85   837.1 2609.39   906.2 2621.89   925.9 2626.71     995 2634.84
#Mann= 3 , 0 , 0
       0      .1       0   625.9    .045       0   640.9      .1       0
Bank Sta=625.9,640.9
XS Rating Curve= 0 ,0
Exp/Cntr=0.3,0.1

Type RM Length L Ch R = 1 ,33390.3 ,318.5,316.2,314.8
XS GIS Cut Line= 3
     1942151.992      260389.973     1942539.297      260526.583
     1942931.122      260644.869
#Sta/Elev= 30
       0 2701.38    29.3 2694.83    68.4  2677.7      88 2666.94   117.3 2649.04
   127.1 2639.36   136.9 2632.12   156.4 2620.58     176 2611.72   205.4 2601.69
   215.1 2597.24   244.5 2592.26     264 2587.62   283.6 2584.61   332.5  2571.8
   381.4  2563.7   403.2 2559.11   410.7 2558.36   418.2 2558.89   480.6 2566.94
   490.6 2569.78   520.5  2574.8   560.4 2583.49   580.4 2590.29   640.3 2606.64
   660.3 2616.27   730.1 2639.48   740.1 2645.04     810 2666.08     820  2671.3
#Mann= 3 , 0 , 0
       0      .1       0   403.2    .045       0   418.2      .1       0
Bank Sta=403.2,418.2
XS Rating Curve= 0 ,0
Exp/Cntr=0.3,0.1

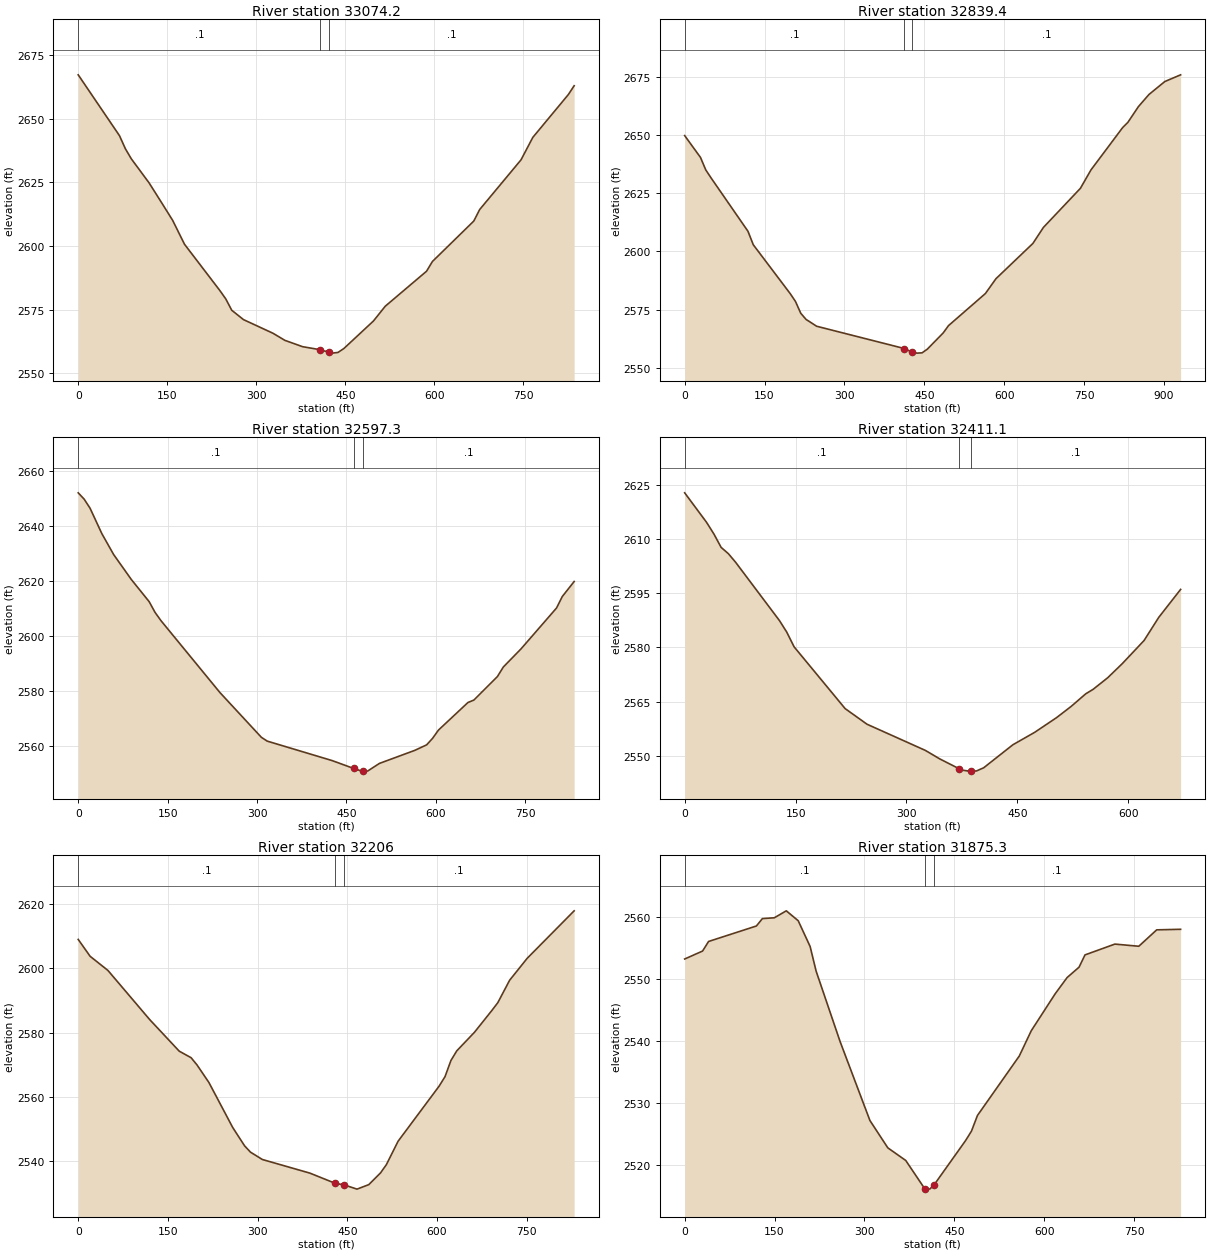
Type RM Length L Ch R = 1 ,33074.2 ,230.3,234.8,239.3
XS GIS Cut Line= 2
     1942033.348       260725.86     1942848.506      260910.092
#Sta/Elev= 30
       0 2667.21    69.6 2643.31    79.6 2638.14    89.5 2634.24   119.4 2624.81
   139.3 2617.49   159.2 2610.07   179.1 2600.72   238.8 2582.51   248.7 2579.25
   258.7 2574.81   278.6 2571.12   328.3 2565.77   348.2    2563   378.1 2560.51
     408 2559.31     423  2558.3   427.8 2557.98   437.8 2558.25   447.7  2559.8
   497.4 2570.57   517.4 2576.39     587 2590.13   596.9 2593.95   666.6 2609.82
   676.5 2614.34   746.2 2633.85   766.1 2642.67   825.8 2659.43   835.7 2662.92
#Mann= 3 , 0 , 0
       0      .1       0     408    .045       0     423      .1       0
Bank Sta=408,423
XS Rating Curve= 0 ,0
Exp/Cntr=0.3,0.1

Type RM Length L Ch R = 1 ,32839.4 ,237.6,242,246.4
XS GIS Cut Line= 2
      1942007.29       260864.81     1942851.316      261258.505
#Sta/Elev= 30
       0  2649.7    29.7 2640.34    39.6 2634.99    49.5 2631.57   118.9 2608.65
   128.8 2602.89   198.2 2581.91   208.1 2578.54     218 2573.48   227.9 2570.86
   247.7 2567.93   412.5 2558.36   427.5 2556.77   435.9 2556.39   445.8 2556.51
   455.8 2558.13   485.5 2565.06   495.4 2568.18   564.7 2581.95   584.6 2588.33
   653.9 2603.44   673.7 2610.32   743.1 2627.08   762.9 2634.96   822.3  2653.1
   832.2 2655.36   852.1 2662.15   871.9 2667.34   901.6 2672.89   931.3 2675.77
#Mann= 3 , 0 , 0
       0      .1       0   412.5    .045       0   427.5      .1       0
Bank Sta=412.5,427.5
XS Rating Curve= 0 ,0
Exp/Cntr=0.3,0.1

Type RM Length L Ch R = 1 ,32597.3 ,186.4,186.2,186
XS GIS Cut Line= 3
     1941847.765      261015.551     1942206.235      261207.157
     1942549.812       261458.65
#Sta/Elev= 30
       0 2652.06     9.9 2649.78    19.8  2646.5    39.7  2637.2    59.5  2629.6
    89.2 2620.52     119  2612.5   128.9 2608.59   138.8 2605.59   237.9  2579.4
   307.3 2563.15   317.2 2561.75   426.3 2554.66   462.3 2551.81   475.8 2550.84
   477.3 2550.84   485.7 2550.87   505.5 2553.65   564.9  2558.4   584.7  2560.4
   594.6 2562.76   604.5 2565.76     654  2575.8   663.9 2576.68   703.5 2585.26
   713.4 2588.72   743.1 2595.31   802.6 2610.16   812.4 2614.38   832.2 2619.81
#Mann= 3 , 0 , 0
       0      .1       0   462.3    .045       0   477.3      .1       0
Bank Sta=462.3,477.3
XS Rating Curve= 0 ,0
Exp/Cntr=0.3,0.1

Type RM Length L Ch R = 1 ,32411.1 ,206.5,204.9,203.4
XS GIS Cut Line= 2
     1941844.287      261177.003     1942391.315      261565.172
#Sta/Elev= 30
       0  2622.7    29.6 2614.55    39.5 2611.34    49.3 2607.63    59.2 2605.87
      69 2603.49   128.2 2587.41   138.1 2584.21     148 2580.16     217  2563.1
   246.6 2558.78   325.5 2551.55   345.2 2549.18   371.7 2546.43   374.8 2546.11
   384.7 2545.82   386.7 2545.83   394.6 2545.86   404.4 2546.74   443.9  2553.1
   473.5 2556.55   503.1 2560.61   522.8 2563.71   542.5 2567.18   552.4 2568.41
   572.1  2571.6   591.8 2575.49   621.4 2581.91   641.2 2588.29   670.8 2596.02
#Mann= 3 , 0 , 0
       0      .1       0   371.7    .045       0   386.7      .1       0
Bank Sta=371.7,386.7
XS Rating Curve= 0 ,0
Exp/Cntr=0.3,0.1

Type RM Length L Ch R = 1 ,32206   ,332.2,330.8,329.3
XS GIS Cut Line= 3
     1941721.036      261274.662     1942019.351      261552.072
     1942378.131      261774.091
#Sta/Elev= 30
       0 2609.01    19.9 2603.76    49.7 2599.35   119.2 2584.12   168.9 2574.22
   188.8 2572.17   198.7 2569.92   218.6 2564.45   258.3 2550.47   278.2 2544.74
   288.1 2542.77     308 2540.48   387.5 2536.24   429.9 2533.06   444.9 2532.57
   466.2 2531.26   485.9 2532.66   505.5  2536.3   515.3 2538.88   534.9 2546.17
   603.6 2563.35   613.4 2566.29   623.2 2571.29     633 2574.31   662.5 2580.07
   691.9 2586.93   701.7 2589.33   721.4  2596.3   750.8 2603.13   829.3 2617.91
#Mann= 3 , 0 , 0
       0      .1       0   429.9    .045       0   444.9      .1       0
Bank Sta=429.9,444.9
XS Rating Curve= 0 ,0
Exp/Cntr=0.3,0.1

Type RM Length L Ch R = 1 ,31875.3 ,344.2,328.2,312.2
XS GIS Cut Line= 2
     1941447.829      261607.995      1942186.87      261980.969
#Sta/Elev= 30
       0  2553.2    29.9 2554.48    39.9 2556.02   119.7 2558.51   129.7  2559.7
   149.6 2559.83   169.6 2560.95   189.5 2559.36   209.4 2555.21   219.4 2551.25
   259.3 2539.95   309.2 2527.22   339.1 2522.82     369 2520.79   400.6 2516.26
   408.9 2516.18   415.6 2516.77   468.8 2523.98   478.7 2525.51   488.7 2528.03
   558.5 2537.59   578.5 2541.66   618.4  2547.6   638.3 2550.21   658.3 2551.89
   668.2 2553.86   718.1  2555.6     758 2555.25   787.9 2557.89   827.8 2557.98
#Mann= 3 , 0 , 0
       0      .1       0   400.6    .045       0   415.6      .1       0
Bank Sta=400.6,415.6
XS Rating Curve= 0 ,0
Exp/Cntr=0.3,0.1

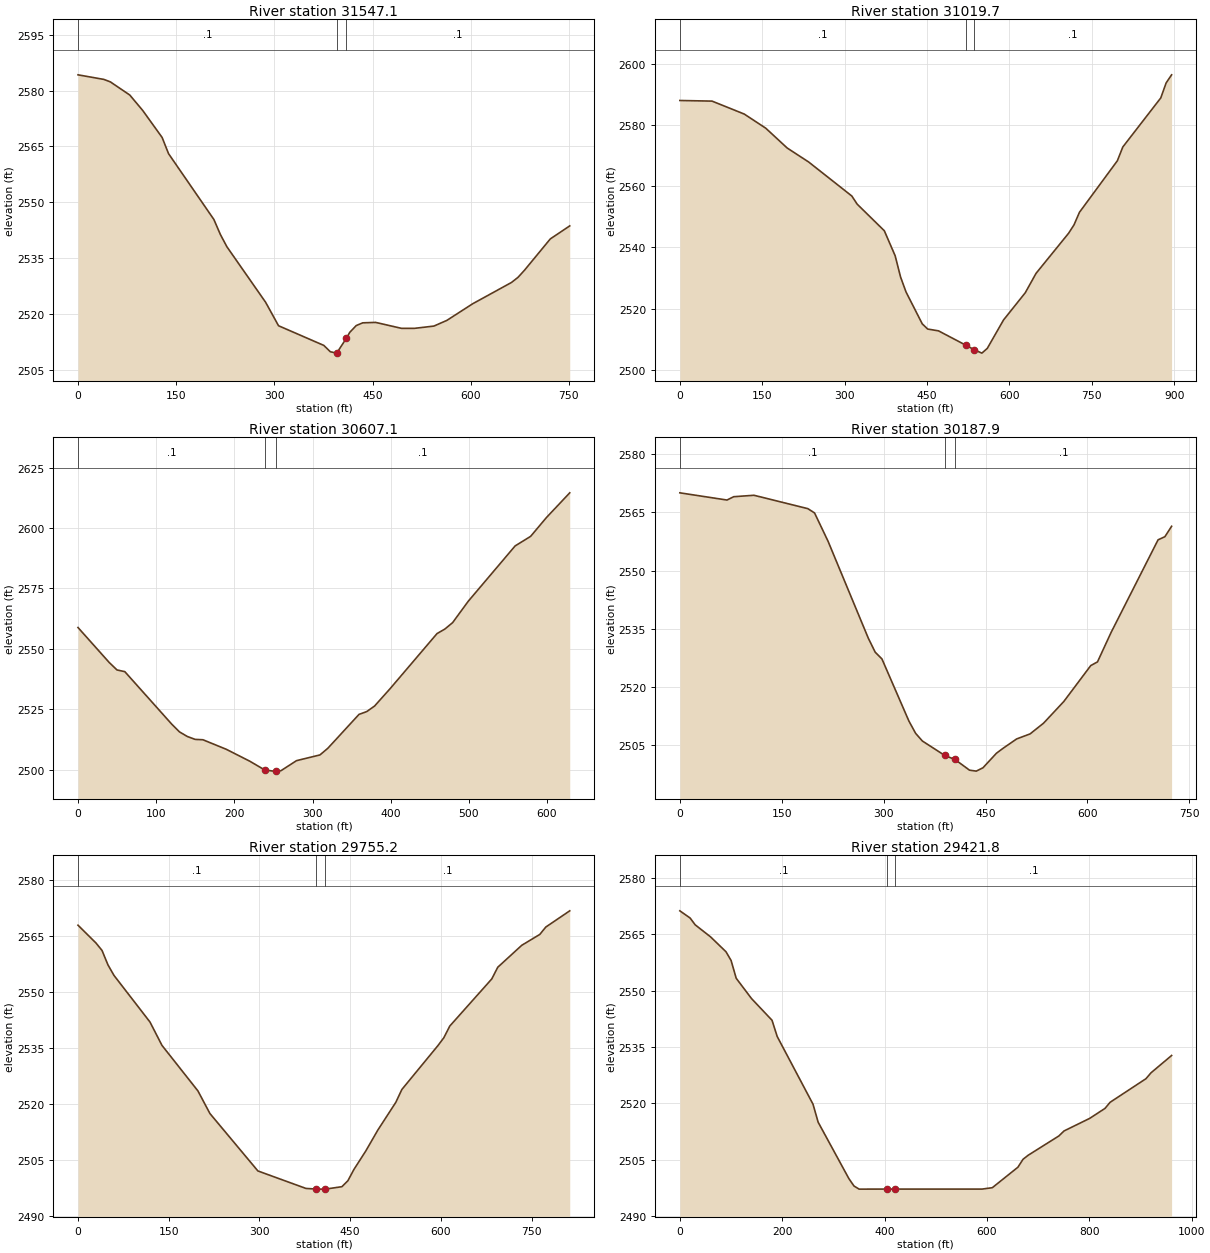
Type RM Length L Ch R = 1 ,31547.1 ,521.2,527.3,533
XS GIS Cut Line= 2
     1941348.369      262164.693     1942080.503      261996.164
#Sta/Elev= 30
       0 2584.22    39.5 2582.99    49.4 2582.33    79.1  2578.8    98.8 2574.67
   128.5 2567.41   138.4 2563.04   207.6 2545.39   217.5 2541.37   227.4 2538.09
   286.7 2523.15   306.4 2516.86   375.6 2511.58   385.5 2509.88   395.2 2509.51
   410.2 2513.54   415.2 2515.09   425.1 2516.91     435 2517.64   454.7 2517.76
   494.3 2516.16     514 2516.16   543.7 2516.77   563.5 2518.29     603 2522.76
   662.3 2528.48   672.2 2529.84   682.1 2531.75   721.6 2540.17   751.3 2543.67
#Mann= 3 , 0 , 0
       0      .1       0   395.2    .045       0   410.2      .1       0
Bank Sta=395.2,410.2
XS Rating Curve= 0 ,0
Exp/Cntr=0.3,0.1

Type RM Length L Ch R = 1 ,31019.7 ,386.7,412.6,438.5
XS GIS Cut Line= 3
     1941489.271      262423.012     1941762.785      262421.631
     1942383.975       262399.85
#Sta/Elev= 30
       0 2588.01    58.6 2587.81   117.2 2583.58   156.3 2578.97   195.4 2572.48
   234.4 2567.92     313  2556.8   322.8 2554.13   372.2 2545.44   391.9 2537.27
   401.8  2530.3   411.6 2525.47   441.2 2515.03   451.1 2513.32   470.8 2512.73
   521.2 2507.98   536.2 2506.53   549.8 2505.45   559.6    2507   589.2 2516.29
   628.7 2525.17   648.4 2531.53   707.6 2544.62   717.5 2547.38   727.4 2551.48
   796.4 2568.32   806.3 2572.82   875.4 2588.85   885.2 2593.77   895.1  2596.4
#Mann= 3 , 0 , 0
       0      .1       0   521.2    .045       0   536.2      .1       0
Bank Sta=521.2,536.2
XS Rating Curve= 0 ,0
Exp/Cntr=0.3,0.1

Type RM Length L Ch R = 1 ,30607.1 ,419.7,419.2,418.6
XS GIS Cut Line= 2
     1941670.232      262471.361     1941954.301      263032.636
#Sta/Elev= 30
       0 2558.84    39.9 2544.38    49.9 2541.27    59.9 2540.57   119.8 2518.88
   129.8 2515.64   139.8 2513.74   149.8 2512.53   159.8 2512.38   189.7 2508.43
   219.7 2503.51   238.6 2499.93   249.6 2499.39   253.6 2499.46   259.6 2499.56
   279.6 2503.73   309.5 2506.09   319.5 2508.81   359.5 2522.88   369.4 2524.04
   379.4 2526.33   399.4 2533.57   459.3 2556.33   469.3 2558.19   479.3 2560.88
   499.3 2569.73   559.2 2592.61   579.1 2596.59   599.1  2604.3   629.1  2614.6
#Mann= 3 , 0 , 0
       0      .1       0   238.6    .045       0   253.6      .1       0
Bank Sta=238.6,253.6
XS Rating Curve= 0 ,0
Exp/Cntr=0.3,0.1

Type RM Length L Ch R = 1 ,30187.9 ,457.6,432.6,407.7
XS GIS Cut Line= 2
     1941193.592       262443.54     1941534.856      263081.933
#Sta/Elev= 30
       0 2570.04    69.4 2568.18    79.3 2569.04   109.1 2569.41   188.4 2565.96
   198.3 2564.85   218.2 2557.54   277.6 2532.48   287.6 2528.94   297.5  2527.2
   337.2 2511.18   347.1 2508.01     357 2506.04     390 2502.31     405 2501.27
   426.4 2498.52   436.3 2498.27   446.2 2499.13   466.1 2502.89     476 2504.18
   495.8 2506.57   515.6 2507.87   535.5 2510.65   565.2 2516.22   604.9 2525.49
   614.8 2526.44   634.6 2533.95     704 2557.92     714 2558.72   723.9 2561.41
#Mann= 3 , 0 , 0
       0      .1       0     390    .045       0     405      .1       0
Bank Sta=390,405
XS Rating Curve= 0 ,0
Exp/Cntr=0.3,0.1

Type RM Length L Ch R = 1 ,29755.2 ,333.1,333.1,333.2
XS GIS Cut Line= 2
     1940800.569      263145.543     1941613.595      263148.239
#Sta/Elev= 30
       0 2567.89    29.8 2563.11    39.7 2561.13    49.6 2557.24    59.5 2554.44
     119 2541.96   138.8 2535.71   198.3  2523.5   218.1 2517.45   297.4 2502.07
   376.8 2497.39   393.8 2497.21   396.6  2497.2   408.8  2497.2   436.3 2497.85
   446.2 2499.45   456.1 2502.45   475.9 2507.45   495.8 2513.04   525.5 2520.46
   535.4 2523.88   594.9 2535.61   604.8 2537.74   614.7 2540.88   684.1  2553.5
     694 2556.63   733.7 2562.51   763.5 2565.42   773.4 2567.39     813 2571.74
#Mann= 3 , 0 , 0
       0      .1       0   393.8    .045       0   408.8      .1       0
Bank Sta=393.8,408.8
XS Rating Curve= 0 ,0
Exp/Cntr=0.3,0.1

Type RM Length L Ch R = 1 ,29421.8 ,397.6,413.2,428.7
XS GIS Cut Line= 2
     1940824.137       263475.64     1941784.887      263481.153
#Sta/Elev= 30
       0 2571.27      20 2569.36      30 2567.54      60 2564.34    90.1 2560.38
   100.1 2558.06   110.1 2553.32   140.1  2547.9   180.1 2542.14   190.2 2537.82
   260.2 2519.79   270.2 2515.01   330.3 2499.98   340.3 2498.01   350.3 2497.19
   405.5  2497.2   420.5  2497.2   590.5  2497.2   610.5 2497.57   660.5 2503.02
   670.5 2505.13   680.5  2506.2   740.6 2511.35   750.6 2512.67   800.6 2516.01
   830.7 2518.68   840.7 2520.31   910.7 2526.58   920.7 2528.17   960.8 2532.76
#Mann= 3 , 0 , 0
       0      .1       0   405.5    .045       0   420.5      .1       0
Bank Sta=405.5,420.5
XS Rating Curve= 0 ,0
Exp/Cntr=0.3,0.1