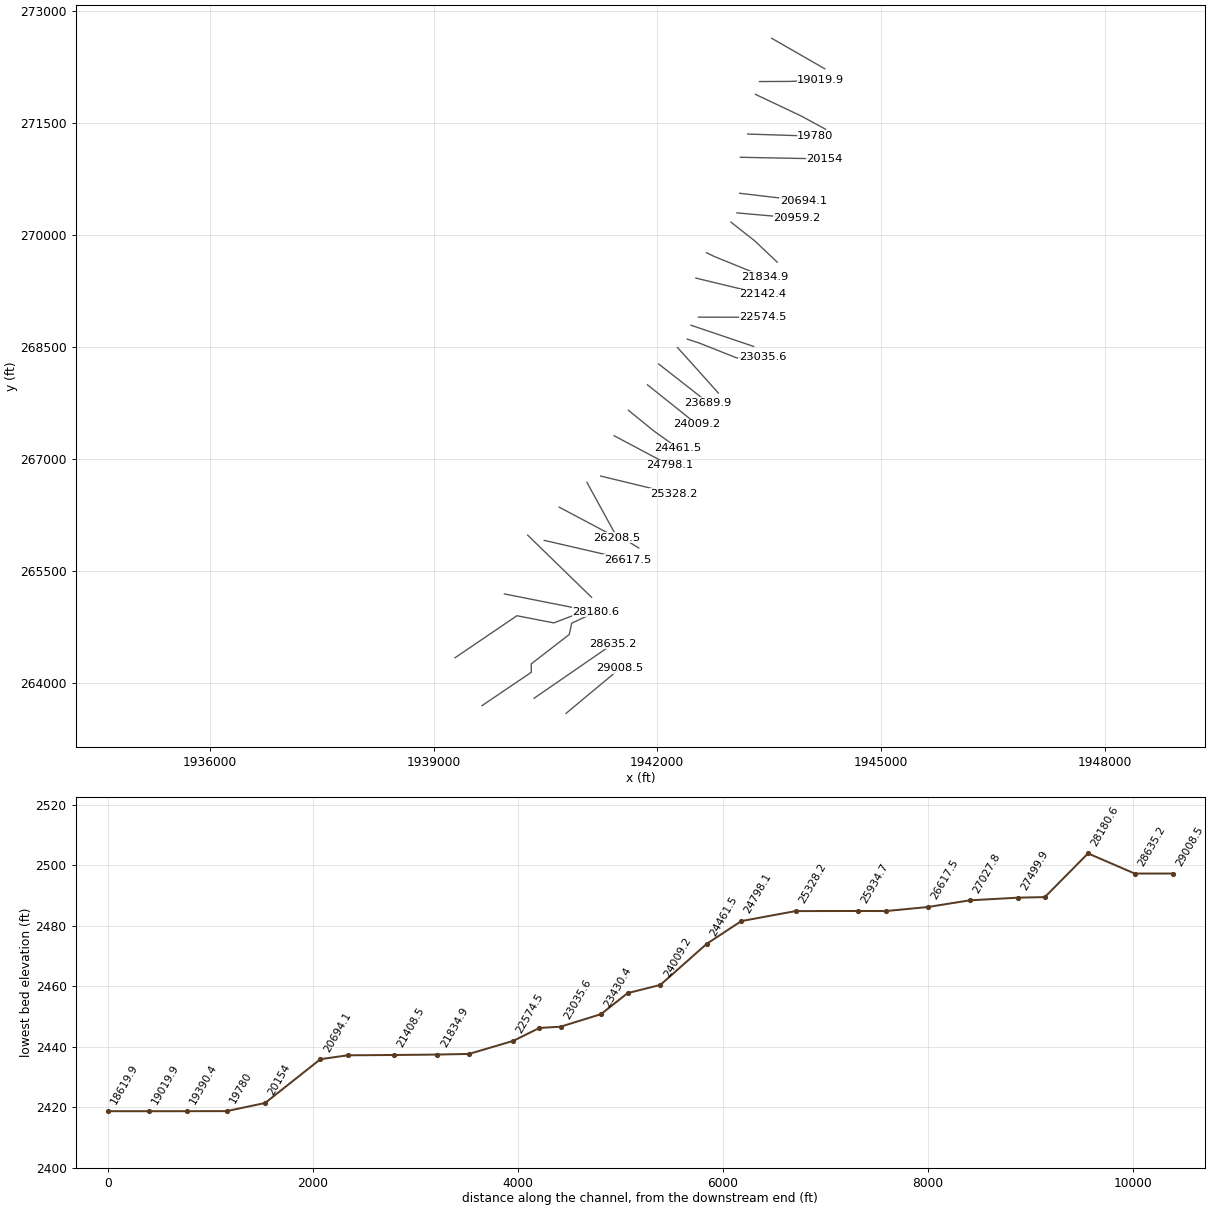
HEC-RAS study LttlBvrCrk.prj: LttlBvrCrk

--- LttlBvrCrk.g01 (geometry) --- (continued)

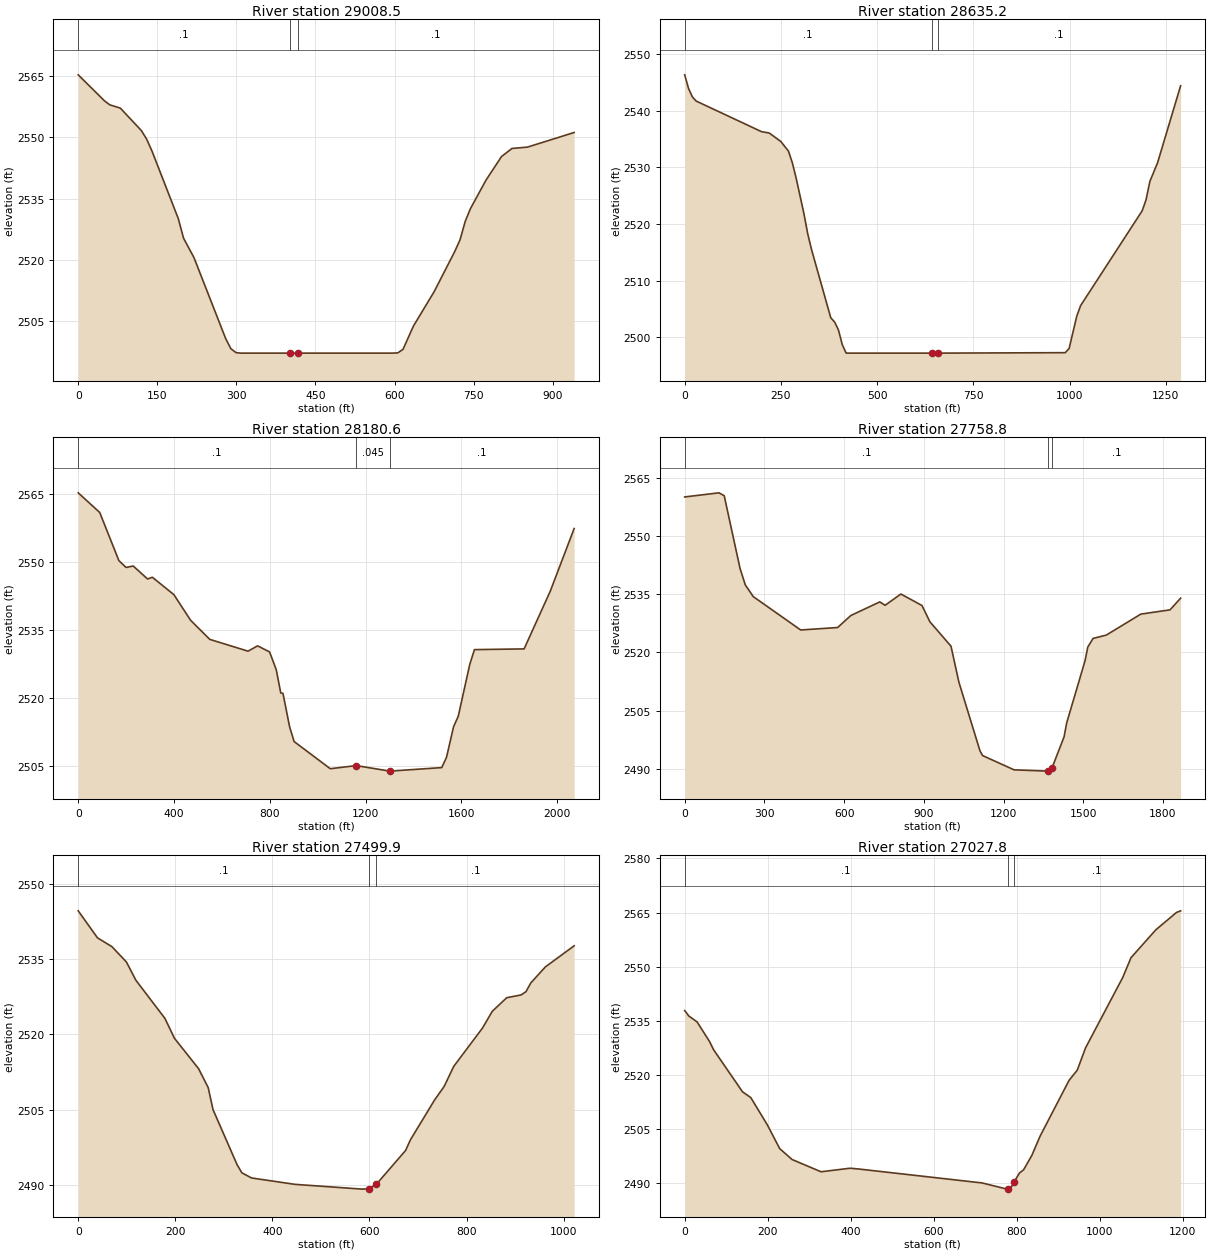
Type RM Length L Ch R = 1 ,29008.5 ,375.2,373.1,371.1
XS GIS Cut Line= 3
     1940777.233       263588.08     1941091.794      263850.266
     1941500.322      264189.804
#Sta/Elev= 30
       0 2565.28    49.9 2558.91    59.9 2557.94    79.9 2557.14   119.8 2551.64
   129.8 2549.55   139.8 2546.68   189.8 2530.12   199.8 2525.32   219.7 2520.53
   279.7 2500.76   289.6 2498.27   299.6 2497.31   309.6  2497.2     402  2497.2
     417  2497.2   596.4  2497.2   606.2 2497.26   616.1 2498.13   635.8 2503.81
   675.1 2512.22   714.4 2522.11   724.3 2524.94   734.1 2529.44     744 2532.55
   773.5 2539.52     803  2545.3   822.7 2547.26   852.2  2547.6   940.7 2551.17
#Mann= 3 , 0 , 0
       0      .1       0     402    .045       0     417      .1       0
Bank Sta=402,417
XS Rating Curve= 0 ,0
Exp/Cntr=0.3,0.1

Type RM Length L Ch R = 1 ,28635.2 ,457.1,454.2,458.2
XS GIS Cut Line= 2
     1940348.247      263790.583      1941409.15      264521.336
#Sta/Elev= 30
       0 2546.35      10 2543.95      20 2542.45      30 2541.71   199.7 2536.31
   219.7 2536.07   249.7 2534.58   269.6 2532.88   279.6 2530.83   289.6 2528.09
   309.6 2521.89   319.6 2518.29   329.6 2515.47   379.5 2503.44   389.5 2502.69
   399.4  2501.3   409.4 2498.69   419.4 2497.21   429.4  2497.2   641.8  2497.2
   656.8  2497.2   988.6 2497.28   998.6 2498.03  1018.6 2503.77  1028.6 2505.61
  1188.4 2522.34  1198.4 2524.28  1208.3 2527.52  1228.3 2530.81  1288.2 2544.42
#Mann= 3 , 0 , 0
       0      .1       0   641.8    .045       0   656.8      .1       0
Bank Sta=641.8,656.8
XS Rating Curve= 0 ,0
Exp/Cntr=0.3,0.1

Type RM Length L Ch R = 1 ,28180.6 ,439.8,421.7,402.1
XS GIS Cut Line= 6
     1939649.143      263691.173     1940311.324      264138.727
      1940309.45      264250.602     1940819.835      264644.804
     1940852.486      264796.247     1941176.954      264948.233
#Sta/Elev= 30
       0 2565.19    89.9 2560.86   169.8 2550.26   199.8 2548.74   229.8 2549.06
   289.7  2546.2   309.7 2546.58   399.6 2542.75   469.6 2537.09   549.5 2532.89
   709.3 2530.29   749.3 2531.46   799.2 2530.13   827.2 2526.21   845.9 2521.09
   855.2 2520.99   883.2 2513.57   901.8 2510.37  1052.9 2504.38  1161.4 2505.07
  1301.8 2503.85  1518.4 2504.63  1538.3  2506.9  1567.8 2513.64  1587.2 2515.92
  1635.6 2527.42    1655 2530.63  1862.4 2530.79  1971.9 2543.54  2071.4 2557.32
#Mann= 3 , 0 , 0
       0      .1       0  1161.4    .045       0  1301.8      .1       0
Bank Sta=1161.4,1301.8
XS Rating Curve= 0 ,0
Exp/Cntr=0.3,0.1

Type RM Length L Ch R = 1 ,27758.8 ,258.9,258.9,258.9
XS GIS Cut Line= 4
     1939288.601      264333.517     1940117.838      264896.453
     1940613.349      264800.425     1940949.026      264928.894
#Sta/Elev= 30
       0 2560.02     129 2561.08   148.8 2560.33   208.4  2541.6   228.2 2537.37
     258 2534.36   436.6 2525.76   575.6 2526.39   625.2 2529.48   734.3 2532.99
   754.2 2532.12   813.7 2535.02   893.1 2532.06   922.9 2527.87  1002.3 2521.58
    1032 2512.32  1111.1 2494.69    1121 2493.42  1239.8 2489.74  1367.8 2489.41
  1382.8  2490.3  1427.8 2498.24  1437.7 2501.84    1507  2517.9    1517 2521.36
  1536.9 2523.58  1586.9 2524.45  1716.7 2529.85  1826.5 2530.94  1866.4 2533.95
#Mann= 3 , 0 , 0
       0      .1       0  1367.8    .045       0  1382.8      .1       0
Bank Sta=1367.8,1382.8
XS Rating Curve= 0 ,0
Exp/Cntr=0.3,0.1

Type RM Length L Ch R = 1 ,27499.9 ,485.1,472.2,459.2
XS GIS Cut Line= 2
     1939950.285      265188.594     1940952.393      264990.097
#Sta/Elev= 30
       0 2544.57    39.7  2539.2    69.4 2537.45    99.2 2534.41     119 2530.74
   178.5  2523.2   198.4 2519.21     248 2513.18   267.8 2509.41   277.7 2505.04
   327.3 2494.09   337.2 2492.47   357.1 2491.45   446.3 2490.18   585.2 2489.23
   599.3 2489.32   614.3 2490.21   674.4 2496.92   684.4 2499.05     734 2506.94
   753.8 2509.65   773.6 2513.64   833.1  2521.3     853  2524.6   882.7 2527.29
   912.5 2527.85   922.4  2528.5   932.3 2530.23   962.1  2533.4  1021.6 2537.62
#Mann= 3 , 0 , 0
       0      .1       0   599.3    .045       0   614.3      .1       0
Bank Sta=599.3,614.3
XS Rating Curve= 0 ,0
Exp/Cntr=0.3,0.1

Type RM Length L Ch R = 1 ,27027.8 ,397.9,410.2,422.5
XS GIS Cut Line= 2
     1940262.478      265976.214     1941119.103      265143.085
#Sta/Elev= 30
       0 2537.84      10 2536.33    29.9 2534.69    59.8 2529.29    69.7 2526.98
   139.4 2515.32   159.3 2513.72   199.2 2506.16     229 2499.57   258.9 2496.55
   328.6 2493.16   398.3 2494.14   418.2 2493.94     717 2490.06   776.7 2488.35
     778 2488.42   786.7 2488.88     793  2490.2   806.6  2492.8   816.6 2493.71
   836.5 2497.69   856.4 2503.03   926.1 2518.47     946 2521.33   965.9 2527.49
  1055.5    2547  1075.5  2552.5  1135.2 2560.21    1185 2565.03    1195 2565.48
#Mann= 3 , 0 , 0
       0      .1       0     778    .045       0     793      .1       0
Bank Sta=778,793
XS Rating Curve= 0 ,0
Exp/Cntr=0.3,0.1

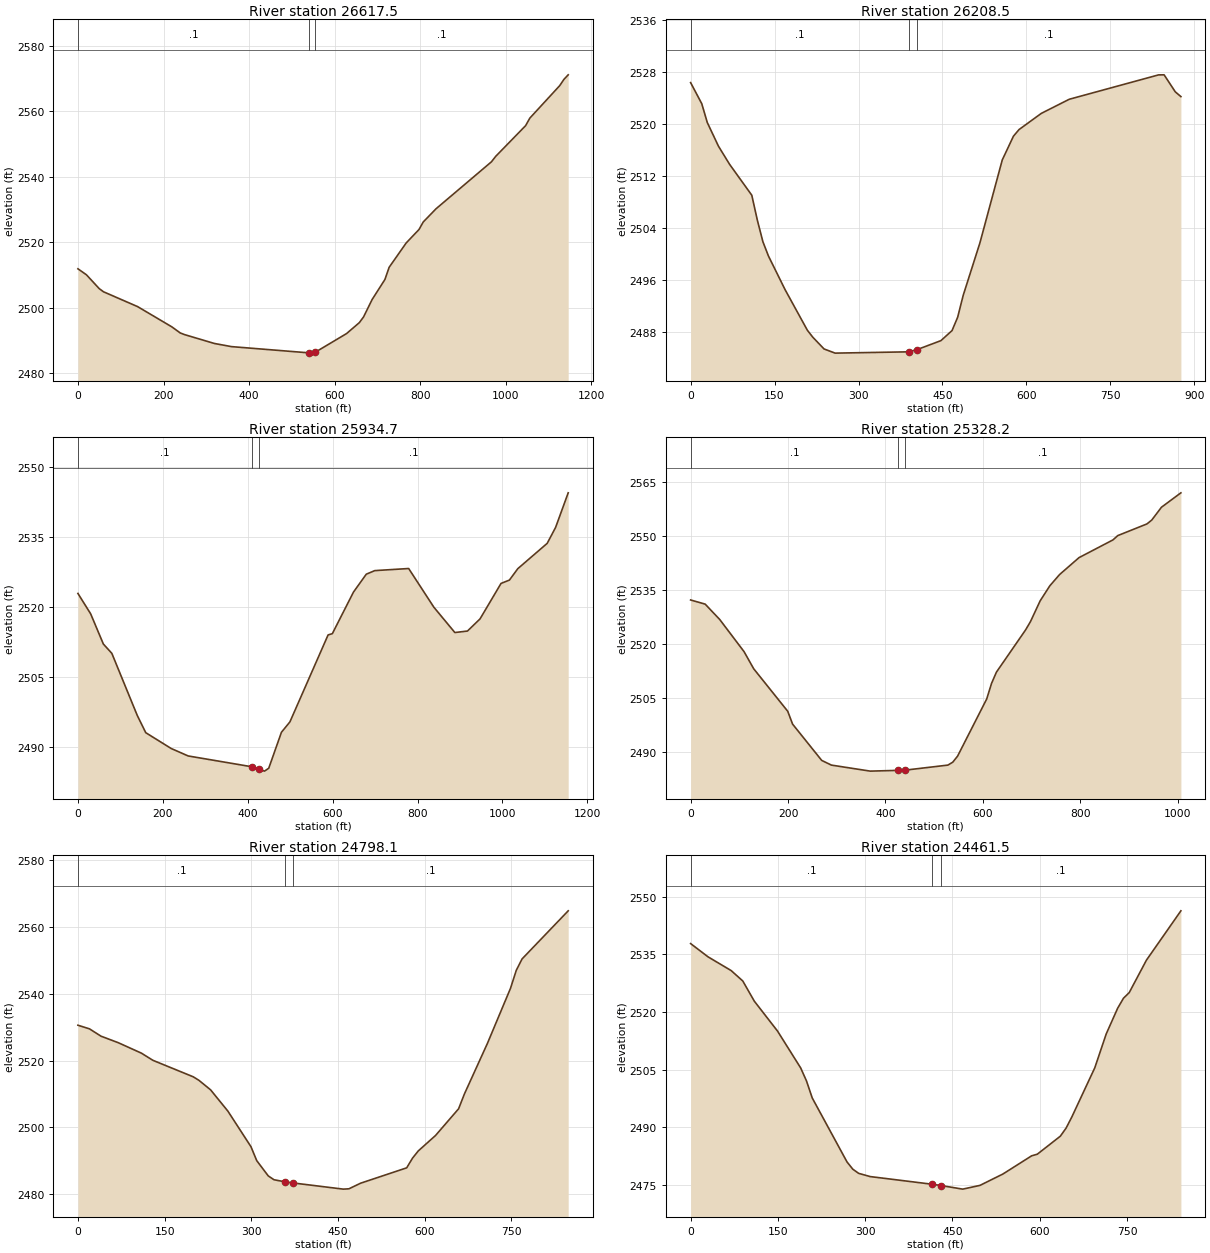
Type RM Length L Ch R = 1 ,26617.5 ,415.1,408.8,402.5
XS GIS Cut Line= 2
       1940485.2      265905.987       1941601.5      265648.365
#Sta/Elev= 30
       0 2511.88    19.9 2510.05    49.8 2505.82    59.8 2504.86   139.5 2500.33
   219.2 2494.17   239.1 2492.29     249 2491.79   318.8 2489.08   358.6 2488.12
     540 2486.21   547.9 2486.13     555 2486.44   627.6 2492.09   657.5 2495.43
   667.5  2497.2   687.4 2502.49   717.3 2508.61   727.2 2512.34   767.1 2519.78
     797 2523.88   806.9 2526.18   836.8 2530.21   966.3 2544.56   976.3 2546.23
    1046 2555.58    1056  2557.9  1125.7  2567.8  1135.7 2569.73  1145.6 2571.11
#Mann= 3 , 0 , 0
       0      .1       0     540    .045       0     555      .1       0
Bank Sta=540,555
XS Rating Curve= 0 ,0
Exp/Cntr=0.3,0.1

Type RM Length L Ch R = 1 ,26208.5 ,287.3,273.8,260.2
XS GIS Cut Line= 3
     1940684.896      266351.083     1941036.021      266165.192
     1941458.741      265940.654
#Sta/Elev= 30
       0 2526.41    19.9 2523.17    29.8 2520.27    49.7 2516.64    69.5 2513.86
   109.3 2509.09   119.2 2505.26   129.1 2501.95     139 2499.75   168.8 2494.56
   208.6 2488.32   218.5 2487.23   238.4 2485.44   258.2  2484.8   389.8    2485
   404.8 2485.35   447.2 2486.72   467.1 2488.27   477.1 2490.31     487 2493.68
     517 2501.79   556.8 2514.51   576.8 2518.17   586.8 2519.19   626.6 2521.68
   676.5 2523.85   836.1  2527.6     846 2527.61     866 2524.99     876 2524.26
#Mann= 3 , 0 , 0
       0      .1       0   389.8    .045       0   404.8      .1       0
Bank Sta=389.8,404.8
XS Rating Curve= 0 ,0
Exp/Cntr=0.3,0.1

Type RM Length L Ch R = 1 ,25934.7 ,588.5,606.7,624.9
XS GIS Cut Line= 3
     1941057.089      266683.453     1941431.587      266000.256
     1941752.121      265804.121
#Sta/Elev= 30
       0 2522.87      30 2518.51    59.9 2512.04    79.9 2510.04   139.8 2496.74
   159.8 2493.05   219.8 2489.66   259.7 2488.07   410.6 2485.74   425.6 2485.29
   439.5 2484.82   449.5 2485.44   479.4 2493.14   499.4 2495.37   589.3 2513.99
   599.3 2514.26   649.2 2523.18   679.2 2526.99   699.2 2527.76   779.1 2528.21
   838.4 2519.93   887.9  2514.5   917.6 2514.82   947.2 2517.42   996.7 2525.02
  1016.4 2525.73  1036.2 2528.18  1105.4  2533.6  1125.2 2537.01  1154.9 2544.42
#Mann= 3 , 0 , 0
       0      .1       0   410.6    .045       0   425.6      .1       0
Bank Sta=410.6,425.6
XS Rating Curve= 0 ,0
Exp/Cntr=0.3,0.1

Type RM Length L Ch R = 1 ,25328.2 ,534.6,529.2,523.1
XS GIS Cut Line= 2
     1941240.498      266768.208     1942219.094      266531.113
#Sta/Elev= 30
       0 2532.21    29.9 2531.06    59.8  2526.8   109.7  2517.9   129.6 2513.14
   199.4 2501.38   209.4 2497.82   269.2 2487.76   289.1 2486.46   368.9 2484.79
     426    2485     441 2485.07   528.4 2486.46   538.4 2487.27   548.3 2488.95
   608.1 2504.79   618.1 2509.13   628.1 2512.23   687.9 2523.91   697.9  2526.2
   717.8 2531.96   737.7 2536.14   757.7 2539.25   797.6 2543.94   867.3 2548.85
   877.3 2550.05   937.1 2553.28   947.1 2554.36     967 2557.91  1006.9  2561.9
#Mann= 3 , 0 , 0
       0      .1       0     426    .045       0     441      .1       0
Bank Sta=426,441
XS Rating Curve= 0 ,0
Exp/Cntr=0.3,0.1

Type RM Length L Ch R = 1 ,24798.1 ,341.5,336.5,332.7
XS GIS Cut Line= 2
     1941421.585      267308.244     1942170.949      266911.145
#Sta/Elev= 30
       0 2530.61      20 2529.52    39.9 2527.33    69.8 2525.37   109.8 2522.24
   129.7 2520.09   199.6 2515.14   209.5 2514.07   229.5 2511.24   259.4 2504.86
   299.3 2494.21   309.3 2490.02   329.2 2485.45   339.2 2484.29   357.7 2483.69
   372.7 2483.32     459 2481.48   468.9 2481.58   488.9 2483.25   568.7 2487.86
   578.7 2490.74   588.7 2492.92   618.6 2497.56   658.5 2505.56   668.5 2509.98
   708.4 2525.18   748.3 2541.68   758.3 2547.07   768.3 2550.48   848.1  2564.9
#Mann= 3 , 0 , 0
       0      .1       0   357.7    .045       0   372.7      .1       0
Bank Sta=357.7,372.7
XS Rating Curve= 0 ,0
Exp/Cntr=0.3,0.1

Type RM Length L Ch R = 1 ,24461.5 ,451.8,452.4,452.3
XS GIS Cut Line= 3
     1941612.514      267650.197      1941952.43       267373.99
      1942281.39      267138.653
#Sta/Elev= 30
       0 2537.77    29.9 2534.33    69.7 2530.75    89.6 2528.06   109.5  2522.8
   149.3 2515.05   189.1 2505.47   199.1 2502.09     209 2497.66   268.8 2481.03
   278.7 2479.16   288.7 2478.08   308.6 2477.24     415 2475.25     430 2474.92
   467.6 2473.98   497.2 2474.95   536.6  2477.9     586 2482.63   595.8 2483.06
   635.3 2487.73   645.2 2489.83     655  2492.7   694.5 2505.49   714.2 2514.31
   733.9    2521   743.8 2523.57   753.7 2525.04   783.3 2533.47   842.5 2546.28
#Mann= 3 , 0 , 0
       0      .1       0     415    .045       0     430      .1       0
Bank Sta=415,430
XS Rating Curve= 0 ,0
Exp/Cntr=0.3,0.1

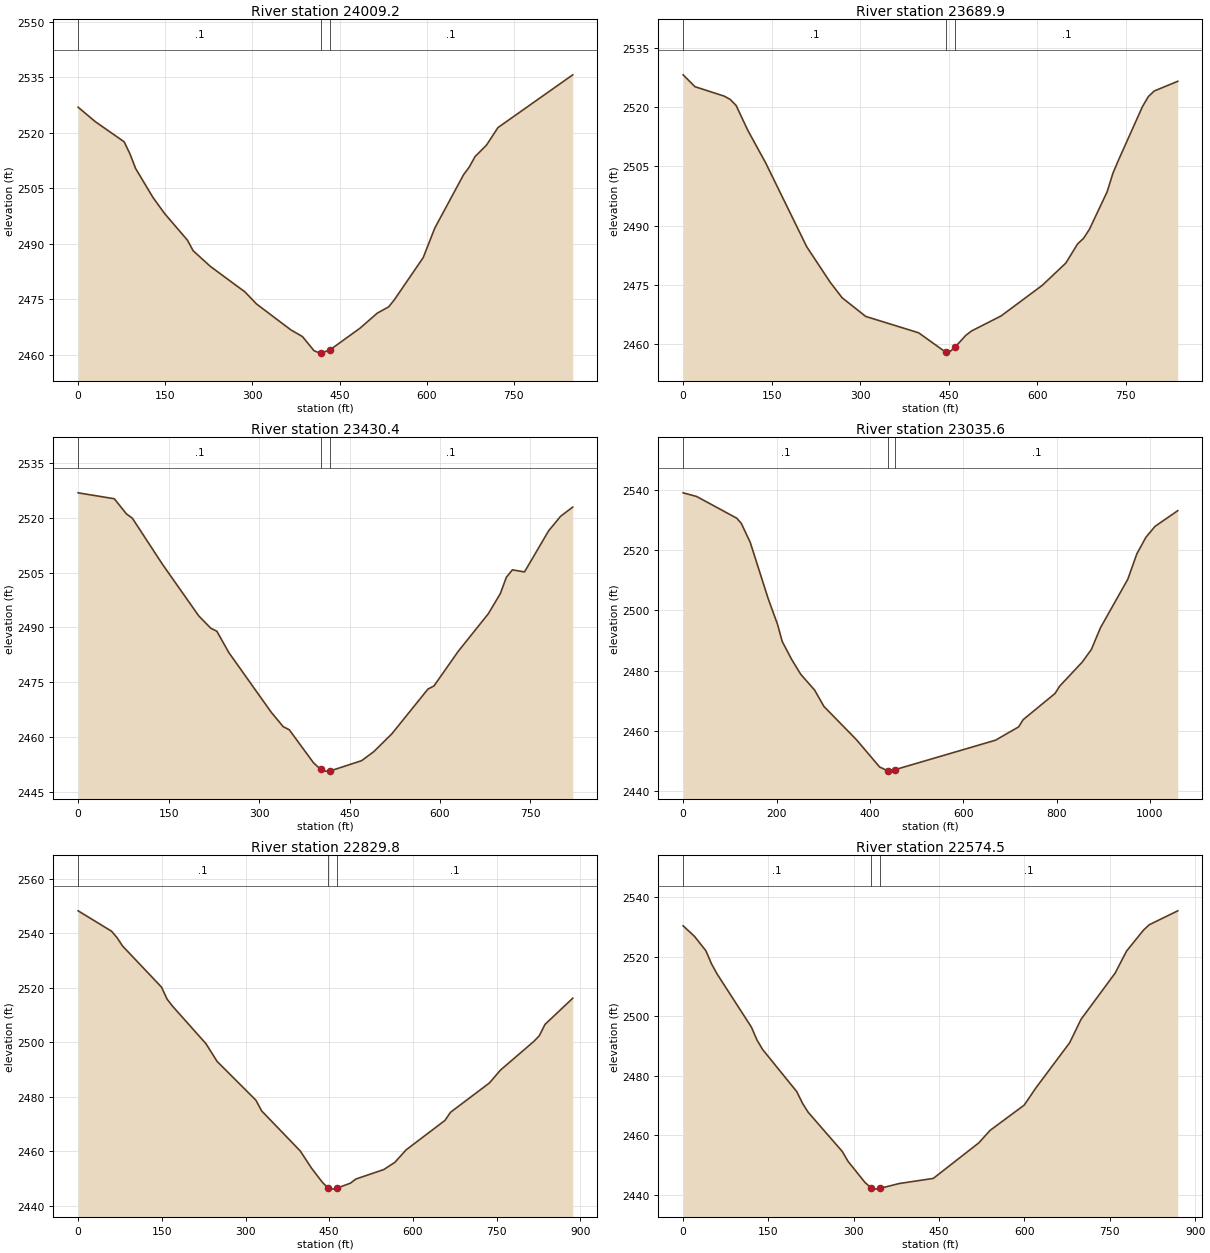
Type RM Length L Ch R = 1 ,24009.2 ,319.1,319.3,319.5
XS GIS Cut Line= 2
      1941868.94       267990.56     1942534.089      267459.036
#Sta/Elev= 30
       0 2526.89    29.7 2522.97    79.2 2517.54    89.1 2514.31      99  2510.3
   128.7 2502.52   148.5 2498.21   188.1 2490.95     198 2488.08   227.7 2483.84
   287.1 2476.96   306.9 2473.71   366.3 2466.67   386.1 2464.88   405.9 2461.08
   415.8  2460.4   417.7 2460.44   432.7 2461.19   485.1 2467.13   514.8  2471.2
   534.6 2472.92   544.5 2474.87     594 2486.23   613.8 2494.17   663.3  2508.6
   673.2  2510.7   683.1 2513.51   702.9 2516.64   722.7 2521.39   851.4 2535.65
#Mann= 3 , 0 , 0
       0      .1       0   417.7    .045       0   432.7      .1       0
Bank Sta=417.7,432.7
XS Rating Curve= 0 ,0
Exp/Cntr=0.3,0.1

Type RM Length L Ch R = 1 ,23689.9 ,263.5,259.5,255.6
XS GIS Cut Line= 2
     1942020.084      268269.044     1942680.091      267753.039
#Sta/Elev= 30
       0 2528.18      20 2525.18    69.8 2522.77    79.8 2521.94    89.8 2520.41
   109.7 2514.08   139.6 2505.93   209.4 2484.62   249.3  2475.6   269.3 2471.72
   309.2 2466.99   398.9 2462.84   445.1  2457.9   448.8 2457.69   460.1 2459.12
   478.7 2462.18   488.7 2463.32   538.6 2467.11   608.4 2474.87   648.3 2480.51
   668.2 2485.36   678.2 2486.76   688.2 2489.06   718.1 2498.52   728.1  2503.3
     738 2506.77   777.9 2520.09   787.9 2522.66   797.9 2524.08   837.8 2526.54
#Mann= 3 , 0 , 0
       0      .1       0   445.1    .045       0   460.1      .1       0
Bank Sta=445.1,460.1
XS Rating Curve= 0 ,0
Exp/Cntr=0.3,0.1

Type RM Length L Ch R = 1 ,23430.4 ,384.1,394.7,405.2
XS GIS Cut Line= 2
     1942271.797      268490.559     1942820.002      267880.529
#Sta/Elev= 30
       0 2526.78      60 2525.16      80 2521.04      90 2519.82     140 2507.21
     200 2493.16     220 2489.78     230 2488.97     250 2483.11   320.1 2466.85
   340.1 2462.88   350.1 2462.05   390.1 2453.06   402.1 2451.22   410.1 2450.74
   417.1 2450.75   470.1  2453.6   490.1 2456.04   520.1 2460.91   580.1 2473.16
   590.1 2474.02   630.1 2483.43   680.1 2493.72   700.1 2499.24   710.1 2503.71
   720.1 2505.73   740.2 2505.17   780.2  2516.4   800.2  2520.4   820.2 2522.88
#Mann= 3 , 0 , 0
       0      .1       0   402.1    .045       0   417.1      .1       0
Bank Sta=402.1,417.1
XS Rating Curve= 0 ,0
Exp/Cntr=0.3,0.1

Type RM Length L Ch R = 1 ,23035.6 ,204.6,205.8,206.9
XS GIS Cut Line= 4
     1942402.703      268602.687     1942566.628      268549.273
     1943065.381      268351.221     1943415.719      268363.247
#Sta/Elev= 30
       0 2539.05    28.7 2537.85   114.9 2530.62   124.5 2528.92   143.7 2522.61
   182.3 2503.85   202.2 2495.36   212.2 2489.69     232 2483.83   251.9 2478.77
   281.7 2473.51   301.6 2468.08   371.2 2457.05   420.8 2447.98   438.9 2446.64
   440.7 2446.59   453.9 2447.08   669.3 2456.87   718.8  2461.3   728.5  2463.7
   796.7 2472.39   806.4 2474.78   855.1 2482.84   874.6 2487.02     894 2494.21
   952.5 2510.31     972 2518.79   991.4 2524.28  1010.9  2527.9  1059.6 2533.12
#Mann= 3 , 0 , 0
       0      .1       0   438.9    .045       0   453.9      .1       0
Bank Sta=438.9,453.9
XS Rating Curve= 0 ,0
Exp/Cntr=0.3,0.1

Type RM Length L Ch R = 1 ,22829.8 ,248,255.3,262.7
XS GIS Cut Line= 2
     1942452.433      268788.714     1943292.315      268505.069
#Sta/Elev= 30
       0 2548.28    59.8 2540.81    69.7 2538.45    79.7 2535.35   149.4  2520.3
   159.4  2515.9   169.3 2513.28   229.1 2499.54     249 2493.05   318.7 2478.79
   328.7 2474.93   398.4 2460.11   418.3 2453.87   438.3 2448.55   448.1 2446.63
   458.2 2446.18   463.1 2446.47   488.1 2448.38     498  2449.9   547.8 2453.36
   567.8 2456.03   587.7 2460.56   657.4 2471.38   667.4 2474.37   737.1 2485.12
     757 2489.86   816.8 2500.38   826.7  2502.5   836.7  2506.6   886.5 2516.22
#Mann= 3 , 0 , 0
       0      .1       0   448.1    .045       0   463.1      .1       0
Bank Sta=448.1,463.1
XS Rating Curve= 0 ,0
Exp/Cntr=0.3,0.1

Type RM Length L Ch R = 1 ,22574.5 ,437.5,432,426.6
XS GIS Cut Line= 2
     1942551.893      268897.382     1943421.245      268895.541
#Sta/Elev= 30
       0  2530.4      20 2526.86      40 2522.02      50 2517.58      60 2514.12
   119.9 2496.39   129.9    2492   139.9 2488.79   199.8 2474.66   209.8 2470.77
   219.8 2467.74   279.8 2454.55   289.8 2451.26   319.8 2444.12   330.3 2442.38
   339.8 2441.91   345.3 2442.13   379.7 2443.79   439.7 2445.51   519.6 2457.44
   539.6 2461.66   599.6 2470.16   619.5 2475.78   679.5 2491.14   699.5 2499.01
   759.4 2514.52   779.4 2521.91   809.4    2529   819.4 2530.77   869.4 2535.44
#Mann= 3 , 0 , 0
       0      .1       0   330.3    .045       0   345.3      .1       0
Bank Sta=330.3,345.3
XS Rating Curve= 0 ,0
Exp/Cntr=0.3,0.1

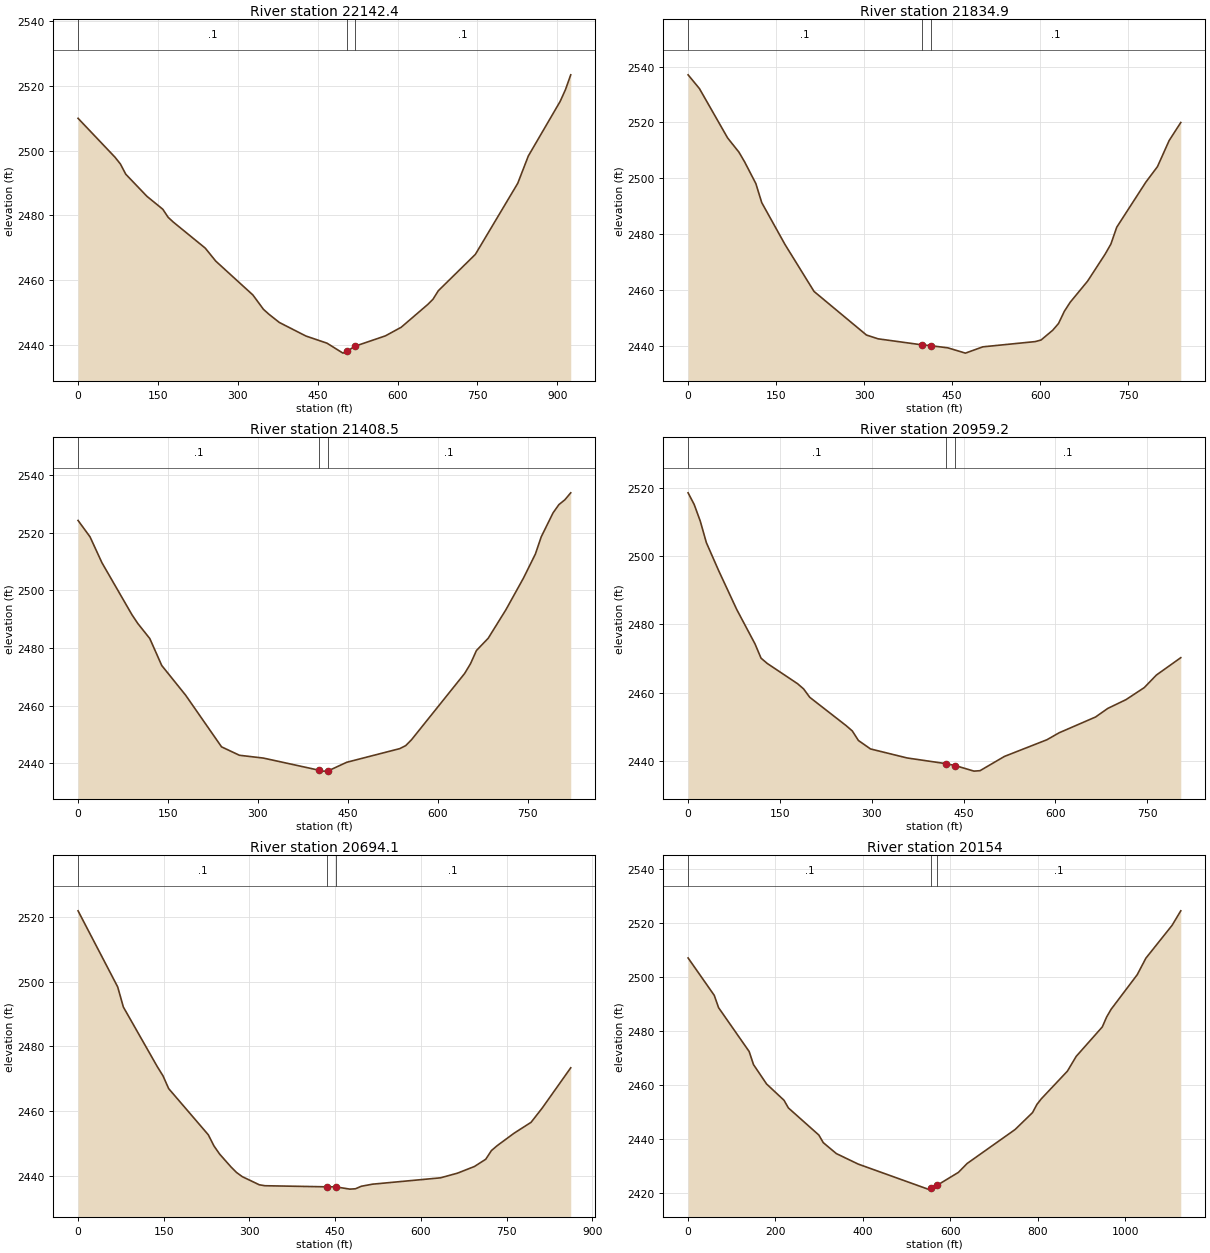
Type RM Length L Ch R = 1 ,22142.4 ,310.6,307.4,304.1
XS GIS Cut Line= 2
      1942518.74      269420.467     1943418.264      269203.414
#Sta/Elev= 30
       0 2509.94    69.6 2497.92    79.6 2495.85    89.6 2492.72   129.4  2485.9
   159.2 2481.92   169.2 2479.44   179.1 2477.94   238.8 2469.96   258.7 2465.93
   328.4  2455.5   348.2 2451.09   358.2 2449.61   378.1 2447.03   427.8 2442.87
   467.6 2440.65   497.5 2437.59     505 2438.14     520 2439.71   577.1  2442.9
   606.9 2445.56   656.7 2452.57   666.6 2454.19   676.6 2456.81   746.2 2468.02
   825.8 2489.92   845.7 2498.35   905.4 2515.14   915.4 2518.77   925.3 2523.34
#Mann= 3 , 0 , 0
       0      .1       0     505    .045       0     520      .1       0
Bank Sta=505,520
XS Rating Curve= 0 ,0
Exp/Cntr=0.3,0.1

Type RM Length L Ch R = 1 ,21834.9 ,432.8,426.3,417.8
XS GIS Cut Line= 3
     1942661.714      269760.309     1942765.547      269709.637
     1943436.646      269437.412
#Sta/Elev= 30
       0 2537.04    19.3 2532.12    67.4 2514.43    86.6 2509.37    96.3 2505.89
   115.5  2498.1   125.5 2491.29   165.1 2476.32   214.7 2459.47     304 2443.87
   323.9 2442.51   398.4 2440.36   413.4 2440.06   442.9 2439.28   472.7 2437.39
   502.4 2439.64   591.7 2441.52   601.6 2442.08   621.5 2445.58   631.4    2448
   641.3 2452.35   651.2 2455.58     681 2463.18   710.8 2472.81   720.7 2476.45
   730.6 2482.46   780.2  2498.6   800.1 2504.18   819.9 2513.48   839.8 2519.97
#Mann= 3 , 0 , 0
       0      .1       0   398.4    .045       0   413.4      .1       0
Bank Sta=398.4,413.4
XS Rating Curve= 0 ,0
Exp/Cntr=0.3,0.1

Type RM Length L Ch R = 1 ,21408.5 ,439.4,449.4,460.5
XS GIS Cut Line= 3
     1942987.933        270170.4     1943309.444      269917.784
     1943609.356      269633.836
#Sta/Elev= 30
       0 2524.24      20 2518.55    39.9 2509.55    89.8 2491.57    99.7 2488.48
   119.7 2483.25   139.6 2473.91   179.5 2463.59   239.4 2445.66   269.3 2442.74
   309.2 2441.77   401.4 2437.58   408.9 2437.24   416.4 2437.25   448.2 2440.31
   536.7 2445.05   546.6 2446.09   556.4 2448.16   644.9 2471.13   654.7 2474.52
   664.6  2479.1   684.2 2483.35   713.7 2493.23   743.2  2504.3   762.9 2512.57
   772.7 2518.57   792.4 2526.87   802.2 2529.75     812 2531.39   821.9 2533.83
#Mann= 3 , 0 , 0
       0      .1       0   401.4    .045       0   416.4      .1       0
Bank Sta=401.4,416.4
XS Rating Curve= 0 ,0
Exp/Cntr=0.3,0.1

Type RM Length L Ch R = 1 ,20959.2 ,262.5,265,268.5
XS GIS Cut Line= 2
      1943068.79       270294.14     1943870.655      270223.512
#Sta/Elev= 30
       0 2518.46     9.9 2515.08    19.9 2510.19    29.8 2503.93    49.7 2495.82
    79.5 2484.36   109.3 2474.33   119.2 2470.15   129.2 2468.62   178.9 2462.68
   188.8 2461.15   198.8 2458.71   258.4 2450.41   268.3 2448.88   278.3 2446.09
   298.1 2443.62   357.8 2440.99   421.8 2439.31   436.8 2438.75   467.1 2437.14
     477 2437.27   516.8 2441.43   586.3 2446.31   606.2 2448.34   665.8 2452.96
   685.7 2455.46   715.5 2458.03   745.3 2461.54   765.2 2465.22     805 2470.29
#Mann= 3 , 0 , 0
       0      .1       0   421.8    .045       0   436.8      .1       0
Bank Sta=421.8,436.8
XS Rating Curve= 0 ,0
Exp/Cntr=0.3,0.1

Type RM Length L Ch R = 1 ,20694.1 ,537.8,540.1,542.4
XS GIS Cut Line= 2
     1943106.289      270556.886     1943962.694       270456.45
#Sta/Elev= 30
       0 2521.87    69.4 2498.35    79.3 2492.14   138.8 2473.68   148.7 2470.87
   158.6 2466.93     228 2452.65   237.9  2449.2   247.8 2446.69   267.6 2442.74
   277.5 2440.99   287.4 2439.72   317.2  2437.2   327.1 2436.91   435.7 2436.57
   450.7 2436.57   475.7 2435.86   485.6 2435.97   495.6 2436.74   515.4 2437.39
   634.3 2439.35     664 2440.79   693.8 2442.86   713.6  2445.1   723.5 2447.78
   733.4 2449.27   763.2 2453.15   792.9 2456.51   812.7 2460.99   862.3 2473.36
#Mann= 3 , 0 , 0
       0      .1       0   435.7    .045       0   450.7      .1       0
Bank Sta=435.7,450.7
XS Rating Curve= 0 ,0
Exp/Cntr=0.3,0.1

Type RM Length L Ch R = 1 ,20154   ,374.2,374,373.7
XS GIS Cut Line= 2
     1943115.498       271039.45     1944242.708      271017.348
#Sta/Elev= 30
       0 2507.15    59.9 2493.27    69.8  2488.7   139.7 2472.45   149.7 2467.58
   179.6 2460.39   219.5 2454.35   229.5 2451.51   299.3 2441.43   309.3 2438.63
   339.2 2434.57   389.1 2430.68   548.8 2421.38   555.7 2421.71   570.7 2422.89
   618.6  2427.6   638.5 2430.89   748.3  2443.5   788.2 2449.78   798.2 2452.81
   808.2 2454.88     868 2465.16     888 2470.62   947.8 2481.56   957.8 2485.26
   967.8 2488.07  1027.6 2500.91  1047.6 2507.08  1107.5 2519.26  1127.4 2524.64
#Mann= 3 , 0 , 0
       0      .1       0   555.7    .045       0   570.7      .1       0
Bank Sta=555.7,570.7
XS Rating Curve= 0 ,0
Exp/Cntr=0.3,0.1

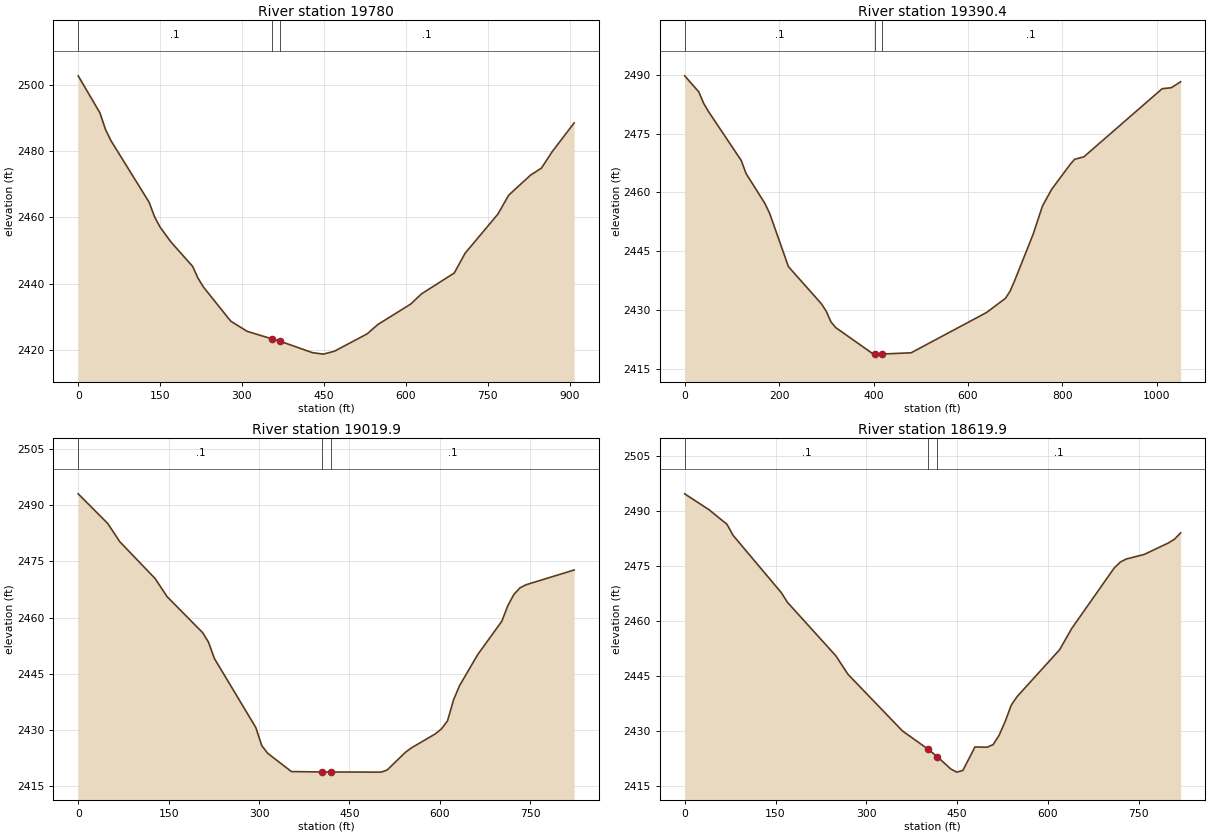
Type RM Length L Ch R = 1 ,19780   ,398.8,389.6,380.3
XS GIS Cut Line= 2
     1943213.116      271350.722     1944121.146      271321.253
#Sta/Elev= 30
       0 2502.71    39.9 2491.49    49.9 2486.55    59.9 2483.16   129.8 2464.58
   139.8 2460.18   149.8 2457.08   169.7  2452.6   209.7 2445.16   219.6 2441.59
   229.6 2438.91   279.5 2428.64   309.5 2425.58   355.2 2423.29   370.2 2422.57
   429.3 2419.13   449.3  2418.7   469.2 2419.57   529.1  2424.8   549.1 2427.66
     609  2433.8     629 2436.91   688.9 2443.19   708.8 2449.17   768.7 2460.94
   788.7  2466.7   828.6 2472.73   848.6 2474.86   868.6 2479.89   908.5  2488.5
#Mann= 3 , 0 , 0
       0      .1       0   355.2    .045       0   370.2      .1       0
Bank Sta=355.2,370.2
XS Rating Curve= 0 ,0
Exp/Cntr=0.3,0.1

Type RM Length L Ch R = 1 ,19390.4 ,360.1,370.4,381.6
XS GIS Cut Line= 3
     1943317.122      271882.403     1943931.436      271592.004
     1944257.443      271415.187
#Sta/Elev= 30
       0 2489.77      30 2485.66      40 2482.79      50 2480.73   119.9 2468.13
   129.9 2464.84   169.9 2457.18   179.9 2454.66   219.8 2441.02   289.8 2431.51
   299.8 2429.64   309.8 2426.93   319.8 2425.47   399.7 2418.68   402.1 2418.68
   417.1  2418.7   479.6 2419.02   639.5 2429.32   679.5 2432.95   689.2 2434.75
     699 2437.49     738 2449.29   757.6 2456.46   777.1 2460.75   816.1 2467.08
   825.9 2468.45   845.4 2469.07  1011.3 2486.48  1030.8 2486.74  1050.4 2488.25
#Mann= 3 , 0 , 0
       0      .1       0   402.1    .045       0   417.1      .1       0
Bank Sta=402.1,417.1
XS Rating Curve= 0 ,0
Exp/Cntr=0.3,0.1

Type RM Length L Ch R = 1 ,19019.9 ,411.9,399.9,387.1
XS GIS Cut Line= 3
     1943371.133      272054.276     1943783.737      272056.035
     1944193.436      272073.487
#Sta/Elev= 30
       0 2493.07    49.1 2485.12    68.8  2480.3   127.7  2470.4   147.4 2465.59
   206.3 2455.97   216.1 2453.43     226 2449.02   294.7 2430.56   304.5 2425.74
   314.4 2423.69   353.7 2418.81   405.1  2418.7   420.1  2418.7   502.6 2418.66
   512.6 2419.24   542.6 2423.94   552.6 2425.13   592.6 2428.91   602.6 2430.22
   612.6 2432.36   622.6 2437.98   632.6 2441.78   662.6 2450.06   702.7    2459
   712.7 2463.18   722.7 2466.15   732.7 2467.91   742.7 2468.75   822.7 2472.71
#Mann= 3 , 0 , 0
       0      .1       0   405.1    .045       0   420.1      .1       0
Bank Sta=405.1,420.1
XS Rating Curve= 0 ,0
Exp/Cntr=0.3,0.1

Type RM Length L Ch R = 1 ,18619.9 ,323.8,329,334.2
XS GIS Cut Line= 3
     1943535.816      272633.165     1943891.039      272429.433
     1944246.262      272225.701
#Sta/Elev= 30
       0 2494.78      40 2490.46    69.9 2486.44    79.9 2483.44   159.8 2467.71
   169.8  2465.1   249.7 2450.48   269.7 2445.43   359.6 2429.95     402 2424.95
     417 2422.94   439.5 2419.53   449.4 2418.68   459.4 2419.14   479.4 2425.57
   499.4 2425.49   509.4 2426.21   519.4 2428.81   529.4 2432.58   539.3    2437
   549.3  2439.4   619.2 2452.16   639.2 2457.97   709.1 2474.45   719.1 2476.09
   729.1 2476.95   759.1 2478.22     799 2481.36     809 2482.39     819 2484.11
#Mann= 3 , 0 , 0
       0      .1       0     402    .045       0     417      .1       0
Bank Sta=402,417
XS Rating Curve= 0 ,0
Exp/Cntr=0.3,0.1