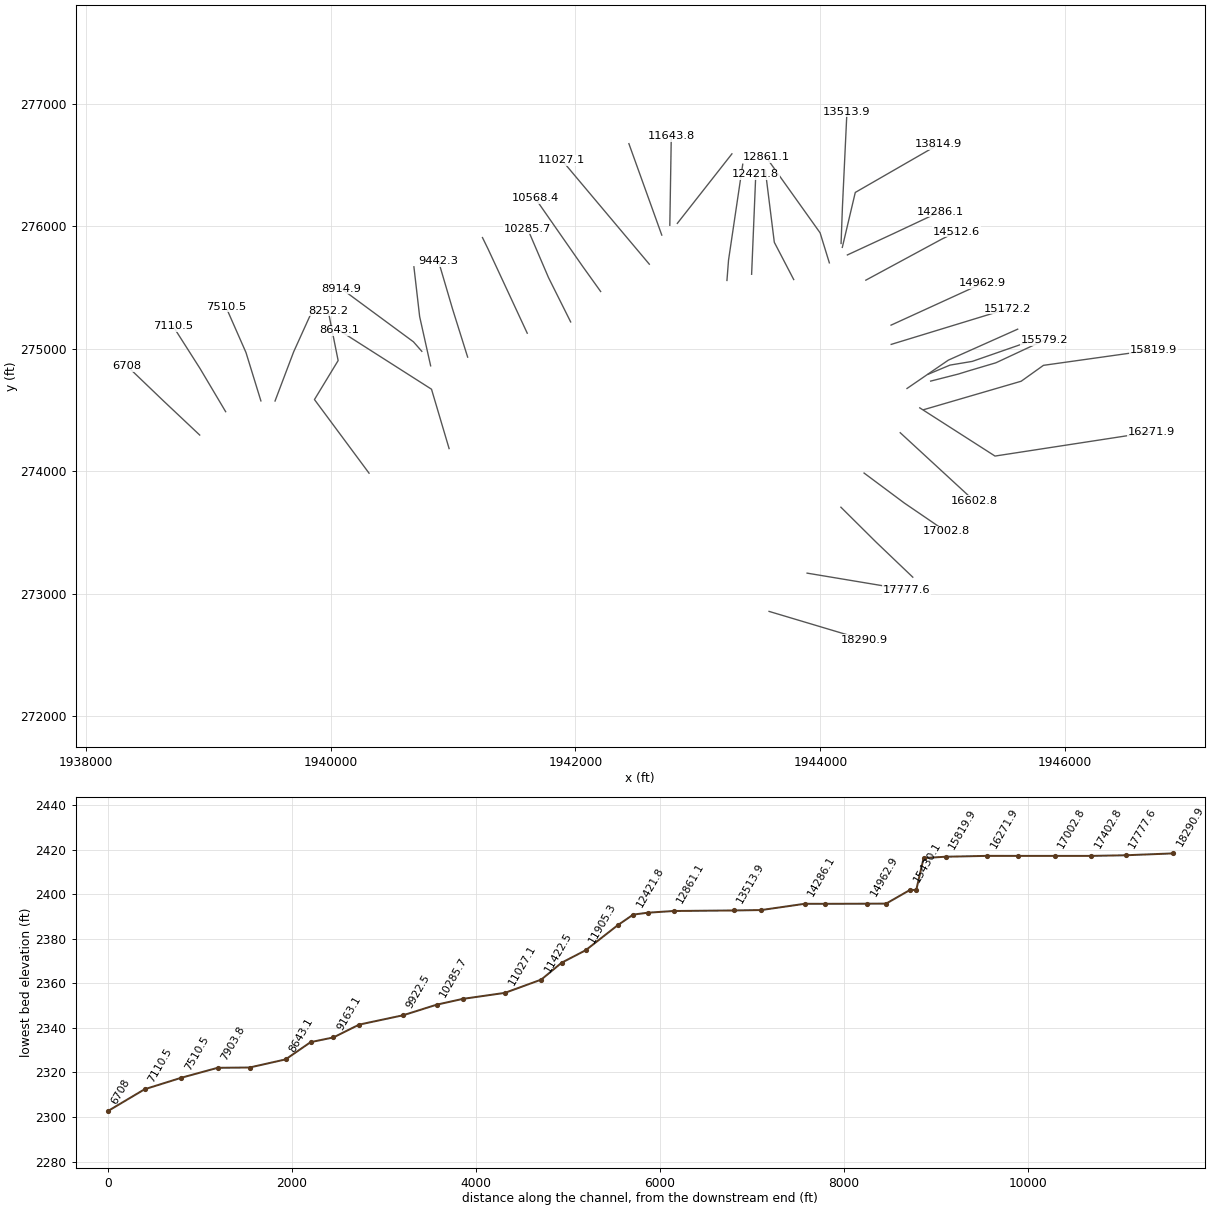
HEC-RAS study LttlBvrCrk.prj: LttlBvrCrk

--- LttlBvrCrk.g01 (geometry) --- (continued)

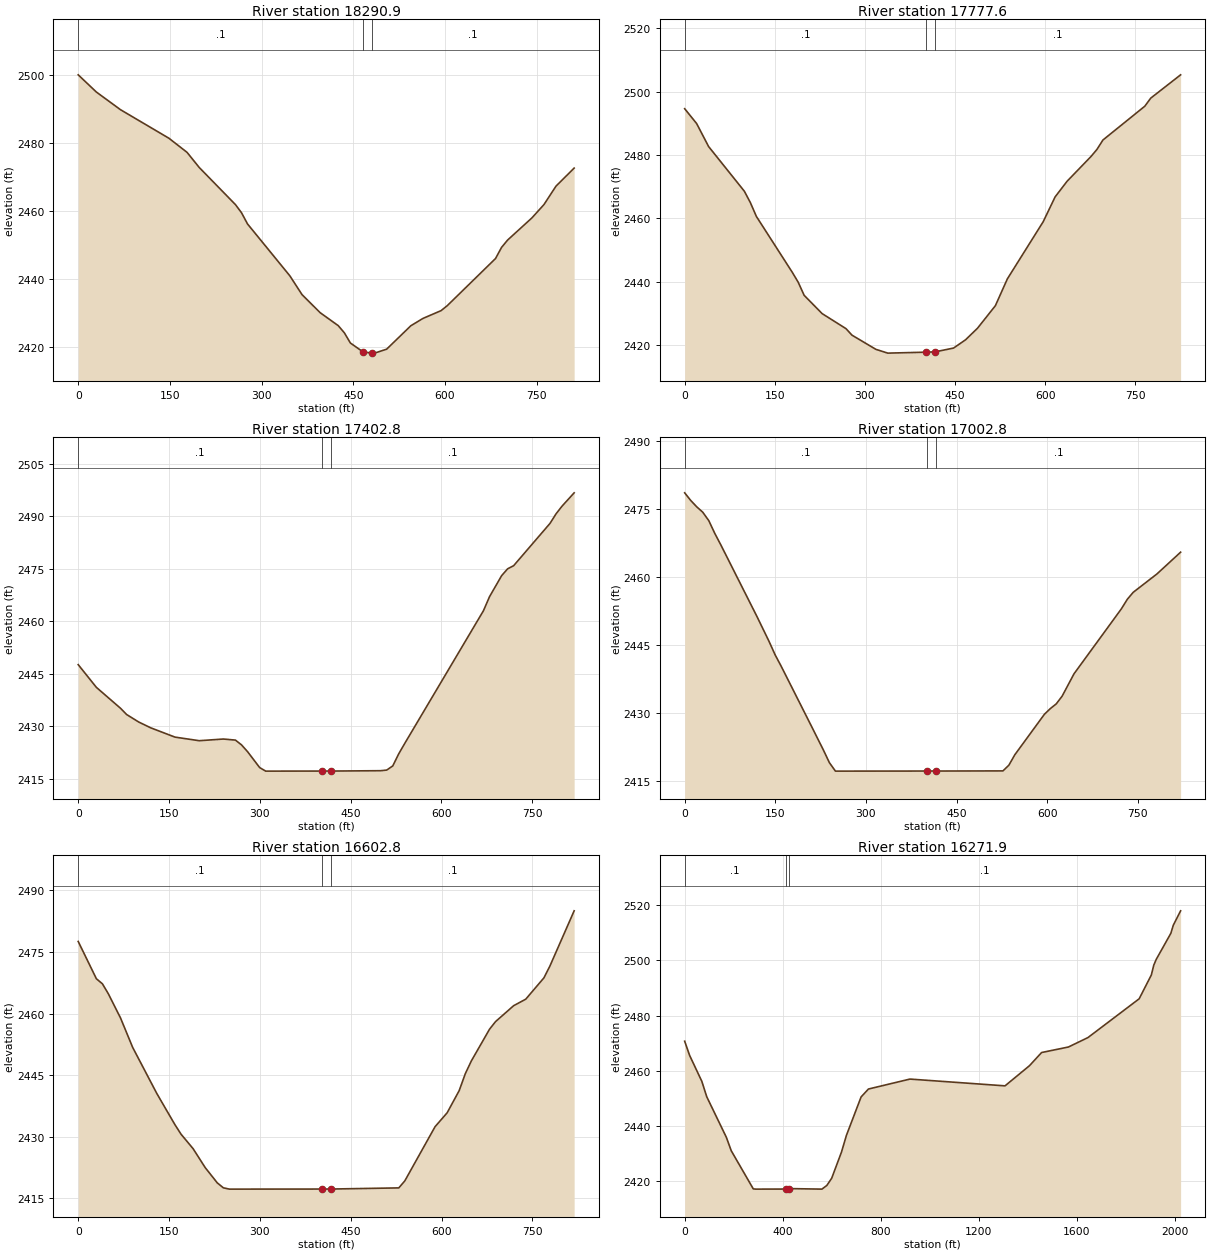
Type RM Length L Ch R = 1 ,18290.9 ,510.3,513.1,516
XS GIS Cut Line= 2
     1943581.485      272855.511     1944358.744      272623.438
#Sta/Elev= 30
       0    2500    29.7 2494.95    69.2 2489.76   148.4 2481.38   178.1 2477.23
   197.8 2472.83   257.2  2461.9   267.1 2459.52     277 2456.21   346.2 2440.99
     366  2435.5   395.7 2430.18   425.4 2426.36   435.3 2424.27   445.2 2421.27
   465.9 2418.66   480.9 2418.31   484.7  2418.3   504.5 2419.46   544.1 2426.34
   563.9 2428.49   593.5 2430.77   603.4 2432.19   682.6 2446.07   692.5 2449.35
   702.4  2451.5   741.9 2457.96   761.7 2461.88   781.5 2467.32   811.2 2472.62
#Mann= 3 , 0 , 0
       0      .1       0   465.9    .045       0   480.9      .1       0
Bank Sta=465.9,480.9
XS Rating Curve= 0 ,0
Exp/Cntr=0.3,0.1

Type RM Length L Ch R = 1 ,17777.6 ,388.5,374.5,360.9
XS GIS Cut Line= 2
     1943892.228      273167.781     1944706.211      273032.086
#Sta/Elev= 30
       0 2494.63    19.9 2489.95    39.8 2482.69    99.4 2468.56   109.4 2464.95
   119.3 2460.63     179    2443   188.9 2439.85   198.8 2435.72   228.7 2429.95
   268.4  2425.2   278.4 2423.14   318.2 2418.66     338 2417.47   401.7 2417.77
   416.7 2417.87   447.4 2419.07   467.3 2421.67   487.2 2425.32     517 2432.45
   536.9  2440.9   596.5 2458.94   616.4  2466.8   636.3 2471.73   676.1 2479.55
     686 2481.79     696 2484.76   765.6 2495.42   775.5 2497.97   825.2 2505.33
#Mann= 3 , 0 , 0
       0      .1       0   401.7    .045       0   416.7      .1       0
Bank Sta=401.7,416.7
XS Rating Curve= 0 ,0
Exp/Cntr=0.3,0.1

Type RM Length L Ch R = 1 ,17402.8 ,396.5,399.7,403.5
XS GIS Cut Line= 3
     1944168.271      273705.847     1944459.119      273417.464
     1944755.405      273134.717
#Sta/Elev= 30
       0  2447.6      30 2441.11    69.9 2435.13    79.9 2433.36    99.9 2431.21
   119.9 2429.54   159.8  2426.9   199.8 2425.87   239.8 2426.35   259.7 2426.04
   269.7 2424.68   279.7 2422.74   299.7 2418.19   309.7 2417.18   402.1  2417.2
   417.1  2417.2   499.5  2417.3   509.5 2417.48   519.5 2418.66   529.4 2422.13
   539.4 2425.12   669.3    2463   679.3    2467   699.3 2473.01   709.2 2474.97
   719.2 2475.87   779.2 2487.94   789.2 2490.68   799.2 2492.89   819.1 2496.68
#Mann= 3 , 0 , 0
       0      .1       0   402.1    .045       0   417.1      .1       0
Bank Sta=402.1,417.1
XS Rating Curve= 0 ,0
Exp/Cntr=0.3,0.1

Type RM Length L Ch R = 1 ,17002.8 ,402.2,399.8,396.5
XS GIS Cut Line= 3
     1944357.468       273984.66     1944685.618      273740.315
       1945025.7      273508.454
#Sta/Elev= 30
       0 2478.51      10 2476.83      20 2475.42    29.9 2474.24    39.9 2472.38
    49.9 2469.55    59.9 2467.02   119.8  2451.2   139.7 2445.75   149.7  2442.8
   159.7  2440.3   209.6 2427.13   229.5 2421.85   239.5 2419.04   249.5 2417.18
   401.6  2417.2   416.6  2417.2   526.7 2417.23   536.5 2418.49   546.3 2420.78
   595.3 2429.71   605.1 2430.96   614.9    2432   624.7 2433.72   644.3 2438.63
   722.7 2452.95   732.5 2455.05   742.3 2456.59   781.5 2460.63   820.7 2465.43
#Mann= 3 , 0 , 0
       0      .1       0   401.6    .045       0   416.6      .1       0
Bank Sta=401.6,416.6
XS Rating Curve= 0 ,0
Exp/Cntr=0.3,0.1

Type RM Length L Ch R = 1 ,16602.8 ,326.8,330.7,334.7
XS GIS Cut Line= 3
     1944652.805      274313.748     1944954.043      274036.356
      1945255.28      273758.964
#Sta/Elev= 30
       0 2477.57      30 2468.48      40 2467.24    49.9 2464.77    69.9 2458.91
    89.9 2451.75   129.8  2440.5   159.8 2432.88   169.8 2430.58   189.8 2427.03
   209.7 2422.43   229.7  2418.7   239.7  2417.5   249.7 2417.18     402  2417.2
     417  2417.2   529.4 2417.48   539.3 2419.18   589.3  2432.4   609.3  2435.8
   629.2 2441.22   639.2 2445.31   649.2 2448.43   679.2 2456.16   689.2 2458.03
   719.1 2461.91   739.1  2463.5   769.1  2468.7     779 2471.59     819 2485.04
#Mann= 3 , 0 , 0
       0      .1       0     402    .045       0     417      .1       0
Bank Sta=402,417
XS Rating Curve= 0 ,0
Exp/Cntr=0.3,0.1

Type RM Length L Ch R = 1 ,16271.9 ,433.6,451.9,470.9
XS GIS Cut Line= 3
     1944812.176      274516.935     1945426.782      274123.371
     1946705.257      274319.779
#Sta/Elev= 30
       0 2470.73      20 2465.64      70 2456.21      90 2450.64     170 2435.96
     190 2431.09   279.9 2417.29   289.9  2417.2   411.7 2417.23   426.7 2417.39
   559.9  2417.2   579.9 2418.53   599.8 2421.14   639.8 2430.63   659.8 2436.64
   719.8 2450.57   749.7 2453.43   918.9 2457.03  1306.9 2454.58  1406.4 2461.85
  1456.2 2466.64  1565.6 2468.64  1645.2 2472.05  1854.2 2486.09  1903.9 2494.72
  1913.8 2498.27  1923.8 2500.35  1983.5  2509.8  1993.4 2512.72  2023.3 2517.93
#Mann= 3 , 0 , 0
       0      .1       0   411.7    .045       0   426.7      .1       0
Bank Sta=411.7,426.7
XS Rating Curve= 0 ,0
Exp/Cntr=0.3,0.1

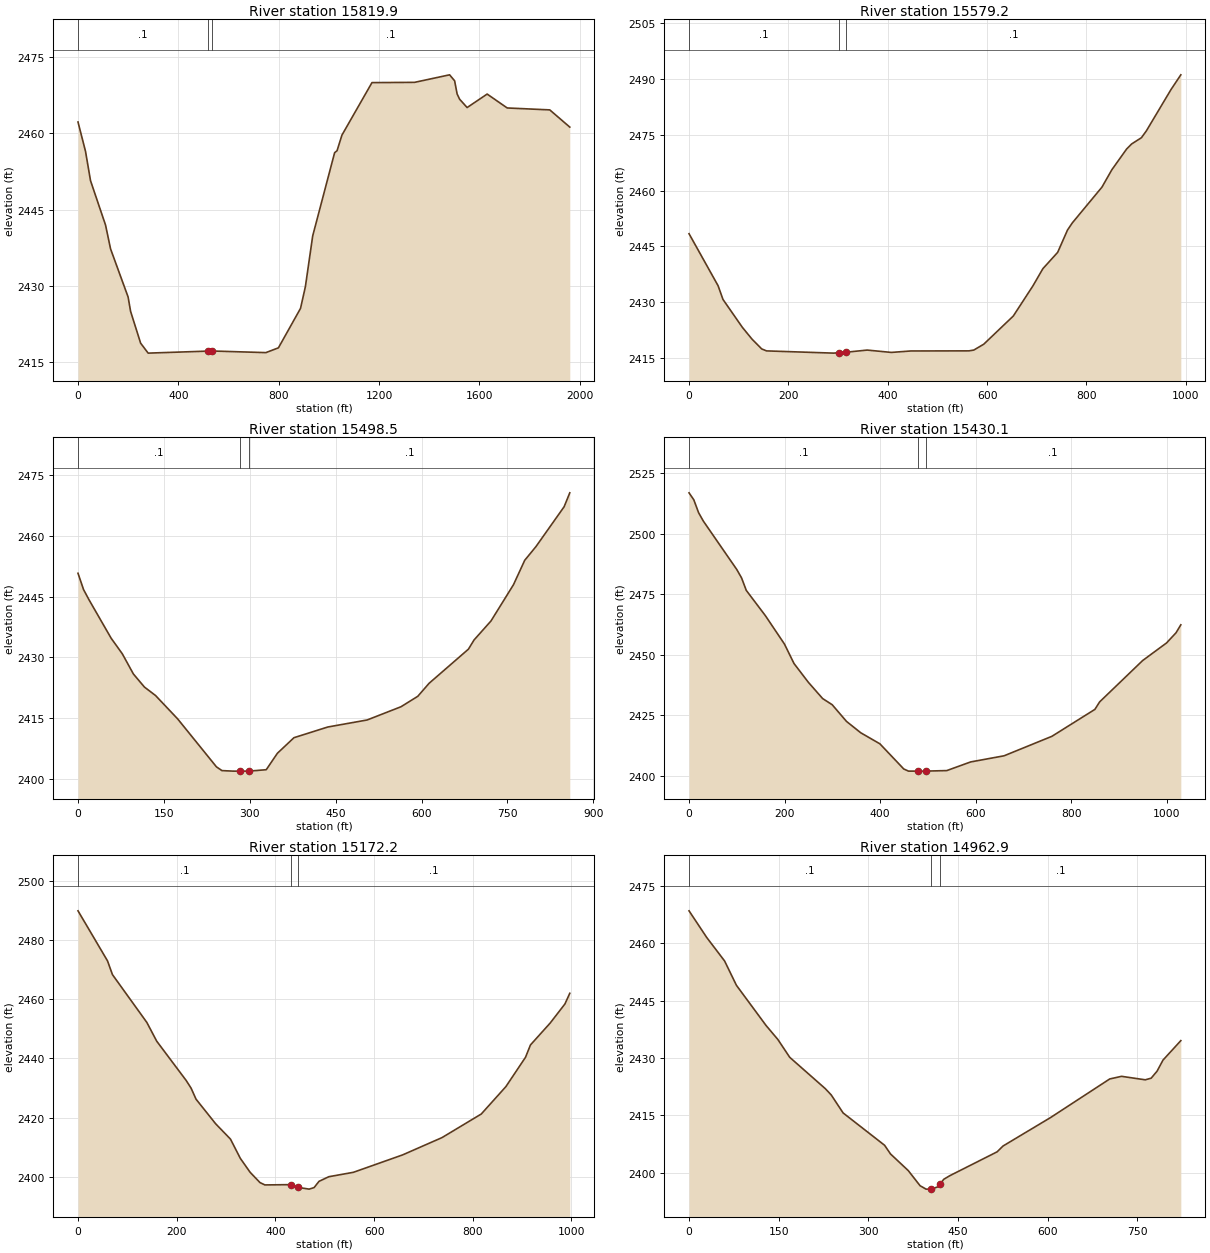
Type RM Length L Ch R = 1 ,15819.9 ,237,240.5,242.3
XS GIS Cut Line= 4
     1944844.992      274502.122      1945640.67      274734.194
     1945822.343      274863.804     1946721.834      274990.211
#Sta/Elev= 30
       0 2462.22      30 2456.44    49.9 2450.69   109.8 2441.97   129.8 2437.29
   199.7 2427.84   209.7    2425   249.6 2418.77   279.6 2416.81   519.1 2417.21
   534.1 2417.23   748.9 2416.91   798.9 2417.85     887  2425.6   906.4 2429.88
   935.6 2439.86  1022.9 2456.19  1032.6 2456.58    1052 2459.64  1171.8 2469.96
  1341.5 2470.01  1481.2 2471.49  1501.2 2470.32  1511.2 2467.73  1521.1  2466.7
  1551.1 2465.06  1630.9 2467.71  1710.8 2464.98  1880.5  2464.6  1960.3 2461.22
#Mann= 3 , 0 , 0
       0      .1       0   519.1    .045       0   534.1      .1       0
Bank Sta=519.1,534.1
XS Rating Curve= 0 ,0
Exp/Cntr=0.3,0.1

Type RM Length L Ch R = 1 ,15579.2 ,83.7,80,76.5
XS GIS Cut Line= 5
     1944901.249      274735.167     1945128.093      274792.862
     1945209.827      274818.212     1945434.048      274884.648
     1945829.605      275069.096
#Sta/Elev= 30
       0 2448.37    58.5 2434.36    68.3 2430.68   107.3 2423.17   126.8 2419.98
   146.3 2417.35     156 2416.82   291.1 2416.22   301.6 2416.35   316.6 2416.47
   358.6 2417.04   407.3 2416.41   446.3  2416.8   563.4 2416.83   573.3 2417.05
   593.2 2418.62   652.7 2426.21   692.4 2434.37   712.2 2438.95     742 2443.35
   761.8 2449.36   771.7 2451.32   831.2 2460.92   851.1  2465.6   880.8 2471.17
   890.8 2472.53   910.6 2474.22   920.5 2476.05   970.1 2487.18   989.9 2491.15
#Mann= 3 , 0 , 0
       0      .1       0   301.6    .045       0   316.6      .1       0
Bank Sta=301.6,316.6
XS Rating Curve= 0 ,0
Exp/Cntr=0.3,0.1

Type RM Length L Ch R = 1 ,15498.5 ,62.5,68.9,75.3
XS GIS Cut Line= 4
     1944881.143      274791.113     1945059.472      274865.854
     1945240.859      274896.012     1945695.858      275054.235
#Sta/Elev= 30
       0  2450.8     9.7 2446.77    19.3 2444.23      58 2434.72    77.3 2430.92
    96.7 2425.92     116 2422.68   135.4 2420.59     174 2414.82   241.8 2402.96
   251.4 2402.03   270.8  2401.9   283.6  2401.9   298.6  2401.9   328.8 2402.25
   348.2  2406.3   377.2 2410.16   436.2  2412.8     505 2414.54     564  2417.8
   593.5 2420.39   613.2  2423.6     682 2432.05   691.8 2434.32   721.3    2439
   760.6 2447.96   780.3 2454.01     800 2457.41   849.1 2467.24     859 2470.68
#Mann= 3 , 0 , 0
       0      .1       0   283.6    .045       0   298.6      .1       0
Bank Sta=283.6,298.6
XS Rating Curve= 0 ,0
Exp/Cntr=0.3,0.1

Type RM Length L Ch R = 1 ,15430.1 ,260.8,258.1,255.3
XS GIS Cut Line= 3
     1944707.979      274674.882     1945045.757      274906.323
     1945611.794      275159.012
#Sta/Elev= 30
       0    2517      10 2514.11      20 2508.79      30 2505.29    99.9 2485.29
   109.9 2481.83   119.8 2476.65   159.8 2466.19   199.7 2454.45   219.7  2446.4
   249.7 2438.64   279.6 2431.91   299.6 2429.36   329.6 2422.45   359.5 2417.74
   399.5 2413.18   449.4 2402.78   459.4 2401.89   480.1  2401.9   495.1  2401.9
   539.4 2402.11   589.4 2405.69   659.4 2408.23   759.4 2416.28   849.4 2427.42
   859.4 2430.53   949.4 2447.63   999.4 2454.91  1019.3 2459.12  1029.3 2462.41
#Mann= 3 , 0 , 0
       0      .1       0   480.1    .045       0   495.1      .1       0
Bank Sta=480.1,495.1
XS Rating Curve= 0 ,0
Exp/Cntr=0.3,0.1

Type RM Length L Ch R = 1 ,15172.2 ,206.2,209.3,212.5
XS GIS Cut Line= 2
     1944579.122      275034.817     1945532.278      275325.944
#Sta/Elev= 30
       0 2489.94    59.8 2473.01    69.8 2468.36   139.5 2452.18   159.5 2445.84
   219.3 2432.52   229.2 2429.93   239.2 2426.21     279 2417.88     309  2412.7
   328.9  2406.2   348.8 2401.48   368.8 2397.99   378.7  2397.2   431.2  2397.3
   446.2 2396.36   468.4 2395.78   478.4  2396.3   488.4 2398.41   508.3 2399.98
   558.1 2401.47   657.8 2407.36   737.5  2413.2   817.2 2421.19   867.1 2430.46
   906.9  2440.4   916.9 2444.56   956.8 2451.96   986.7 2458.42   996.6 2462.04
#Mann= 3 , 0 , 0
       0      .1       0   431.2    .045       0   446.2      .1       0
Bank Sta=431.2,446.2
XS Rating Curve= 0 ,0
Exp/Cntr=0.3,0.1

Type RM Length L Ch R = 1 ,14962.9 ,448.8,450.3,451.8
XS GIS Cut Line= 2
     1944577.798      275191.881     1945326.208      275533.908
#Sta/Elev= 30
       0 2468.49    29.7  2461.5    59.5 2455.38    79.3 2449.02   128.9 2438.51
   148.7 2434.84   168.5 2430.19     228    2422   237.9 2420.36   257.8 2415.65
   327.2  2407.2   337.1 2404.93   366.8 2400.58   386.6 2396.62   396.6 2395.73
   405.6 2395.74   416.4 2396.33   420.6 2397.17   426.3 2398.31   436.2 2399.23
   515.5 2405.48   525.4    2407   604.8 2414.43   703.9 2424.53   723.7 2425.22
   763.4 2424.31   773.3 2424.74   783.2 2426.58   793.1 2429.47   822.9 2434.55
#Mann= 3 , 0 , 0
       0      .1       0   405.6    .045       0   420.6      .1       0
Bank Sta=405.6,420.6
XS Rating Curve= 0 ,0
Exp/Cntr=0.3,0.1

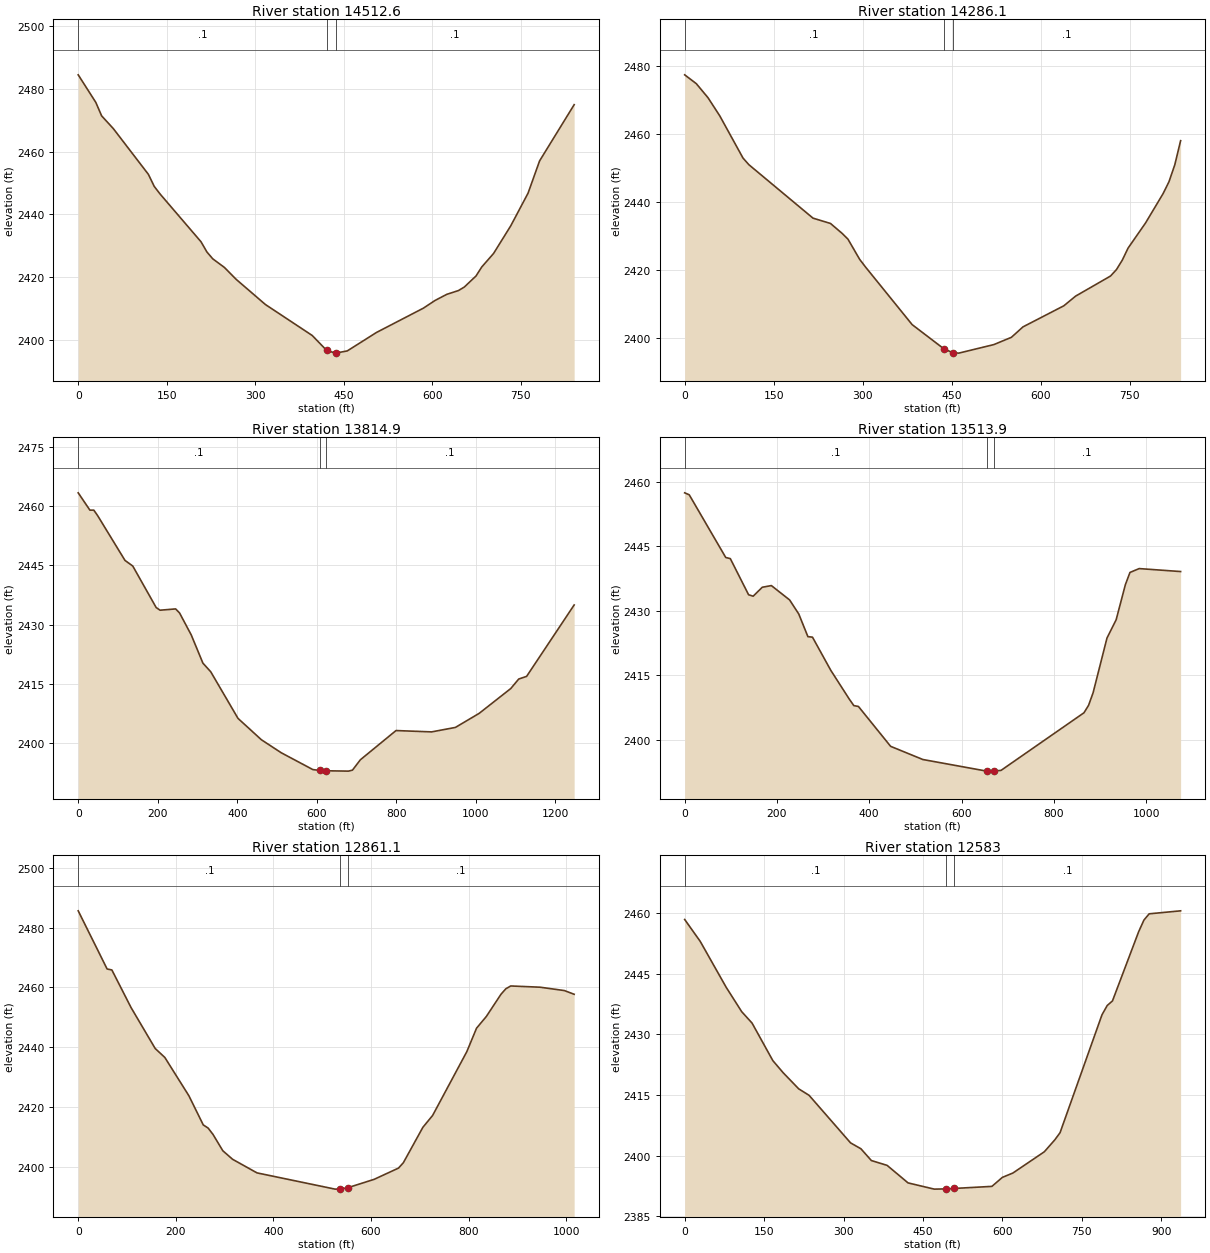
Type RM Length L Ch R = 1 ,14512.6 ,227.9,226.6,225.3
XS GIS Cut Line= 3
     1944371.914      275559.053     1944991.465      275893.693
     1945113.718       275954.82
#Sta/Elev= 30
       0 2484.56    29.8 2475.77    39.7 2471.46    59.5 2467.39     119 2452.77
   128.9 2448.92   138.8  2446.5   208.3 2431.22   218.2 2427.98   228.1  2425.8
   247.9 2423.04   267.8 2419.24   317.4  2411.2   396.7 2401.32   421.4 2396.52
   436.4 2395.68   456.2 2396.39   505.8 2402.29   585.1 2410.03     605  2412.5
   624.8 2414.45   644.6 2415.66   654.6 2416.79   674.4 2420.31   684.3 2423.23
   704.2 2427.51   733.4 2436.36   762.7 2446.79   782.2 2457.07   840.8 2475.02
#Mann= 3 , 0 , 0
       0      .1       0   421.4    .045       0   436.4      .1       0
Bank Sta=421.4,436.4
XS Rating Curve= 0 ,0
Exp/Cntr=0.3,0.1

Type RM Length L Ch R = 1 ,14286.1 ,471.7,470.9,470
XS GIS Cut Line= 3
     1944221.228      275764.822     1944595.699      275938.243
     1944978.446      276117.979
#Sta/Elev= 30
       0 2477.28    19.6 2474.69    39.3 2470.57      59 2465.29    98.3 2452.87
   108.1 2450.94   216.2 2435.26   245.6 2433.71   265.3 2430.79   275.1  2429.1
   294.8 2423.18   304.6 2420.95   383.2 2404.05   436.4 2396.99   451.4 2395.83
   461.8 2395.69   520.8 2398.19   550.4 2400.32     570 2403.39   638.8 2409.57
   658.5 2412.39   717.5  2418.3   727.4 2420.18   737.2 2422.94     747 2426.48
   776.5 2433.87     806 2442.46   815.9 2445.94   825.7 2450.91   835.5 2457.97
#Mann= 3 , 0 , 0
       0      .1       0   436.4    .045       0   451.4      .1       0
Bank Sta=436.4,451.4
XS Rating Curve= 0 ,0
Exp/Cntr=0.3,0.1

Type RM Length L Ch R = 1 ,13814.9 ,275.7,301,326.3
XS GIS Cut Line= 3
     1944179.788      275826.712     1944285.693      276275.013
     1944967.176      276667.326
#Sta/Elev= 30
       0  2463.4    29.4 2459.01    39.2 2459.02      49  2457.6   117.6 2446.28
   137.2 2444.85     196 2434.34   205.8 2433.66     245 2433.99   254.8 2432.97
   284.2  2427.4   313.6 2420.24   333.2 2418.07   401.8 2406.25   460.6 2400.84
   510.4 2397.55     590 2393.28   607.7 2393.06   622.7 2392.98   679.6 2392.89
   689.6 2393.14   709.5 2395.77   799.1 2403.17   888.6 2402.83   948.4 2403.96
  1008.1 2407.52  1087.7 2413.82  1107.6 2416.22  1127.5  2416.9    1247 2434.99
#Mann= 3 , 0 , 0
       0      .1       0   607.7    .045       0   622.7      .1       0
Bank Sta=607.7,622.7
XS Rating Curve= 0 ,0
Exp/Cntr=0.3,0.1

Type RM Length L Ch R = 1 ,13513.9 ,635.9,652.5,668.5
XS GIS Cut Line= 3
     1944169.657      275858.756     1944180.708      276155.293
     1944217.545      276932.552
#Sta/Elev= 30
       0 2457.39     9.9 2456.93      89 2442.36    98.9  2442.1   138.5  2433.7
   148.4 2433.36   168.2 2435.44   187.9 2435.83   227.5 2432.49   247.3 2429.22
   267.1 2423.96     277 2423.84   316.7 2416.13   356.6 2409.47   366.6 2407.93
   376.6 2407.73   446.4 2398.46   516.2  2395.4   654.6  2392.7   669.6  2392.7
   685.8 2392.88   865.4 2406.26   875.4 2407.99   885.3 2410.95   915.3 2423.63
   935.2 2427.89   955.2 2436.05   965.1 2438.88   985.1 2439.78  1074.9 2439.09
#Mann= 3 , 0 , 0
       0      .1       0   654.6    .045       0   669.6      .1       0
Bank Sta=654.6,669.6
XS Rating Curve= 0 ,0
Exp/Cntr=0.3,0.1

Type RM Length L Ch R = 1 ,12861.1 ,289.8,278,266.2
XS GIS Cut Line= 3
      1944073.88      275700.357     1943998.365      275945.323
     1943557.052      276564.169
#Sta/Elev= 30
       0 2485.64    59.2 2466.17      69 2465.84   108.4 2453.22   157.8 2439.54
   177.5 2436.55   226.8 2423.73   256.3 2413.96   266.3  2412.9   276.3 2410.76
   296.4  2405.3   316.4 2402.45   366.4  2397.9   526.4 2392.46   537.5 2392.51
   552.5 2392.93   606.4 2395.73   656.4  2399.5   666.4 2401.31   706.4 2413.16
   726.4 2417.14   796.4 2438.48   816.4 2446.35   836.4 2450.26   866.4 2457.69
   876.4 2459.54   886.4 2460.48   946.4 2460.07   996.4 2458.94  1016.4  2457.7
#Mann= 3 , 0 , 0
       0      .1       0   537.5    .045       0   552.5      .1       0
Bank Sta=537.5,552.5
XS Rating Curve= 0 ,0
Exp/Cntr=0.3,0.1

Type RM Length L Ch R = 1 ,12583   ,164.3,161.3,158.4
XS GIS Cut Line= 3
     1943782.869       275564.06      1943624.47      275867.965
     1943550.796      276457.356
#Sta/Elev= 30
       0 2458.39    29.4 2452.97    78.3 2441.64   107.7 2435.59   127.3 2432.76
   166.5 2423.49     186 2420.49   215.4  2416.5     235  2414.9   313.3 2403.14
   332.9 2401.68   352.6 2398.77   382.3 2397.58   421.9 2393.24   471.4  2391.7
   494.5 2391.76   509.5 2391.87   580.3 2392.38   600.1 2394.61   619.9 2395.68
   679.3 2400.94   699.1 2403.89     709 2405.66   788.2 2434.82   798.1 2437.12
     808 2438.25   857.5 2455.38   867.4 2458.24   877.3 2459.79   936.7 2460.53
#Mann= 3 , 0 , 0
       0      .1       0   494.5    .045       0   509.5      .1       0
Bank Sta=494.5,509.5
XS Rating Curve= 0 ,0
Exp/Cntr=0.3,0.1

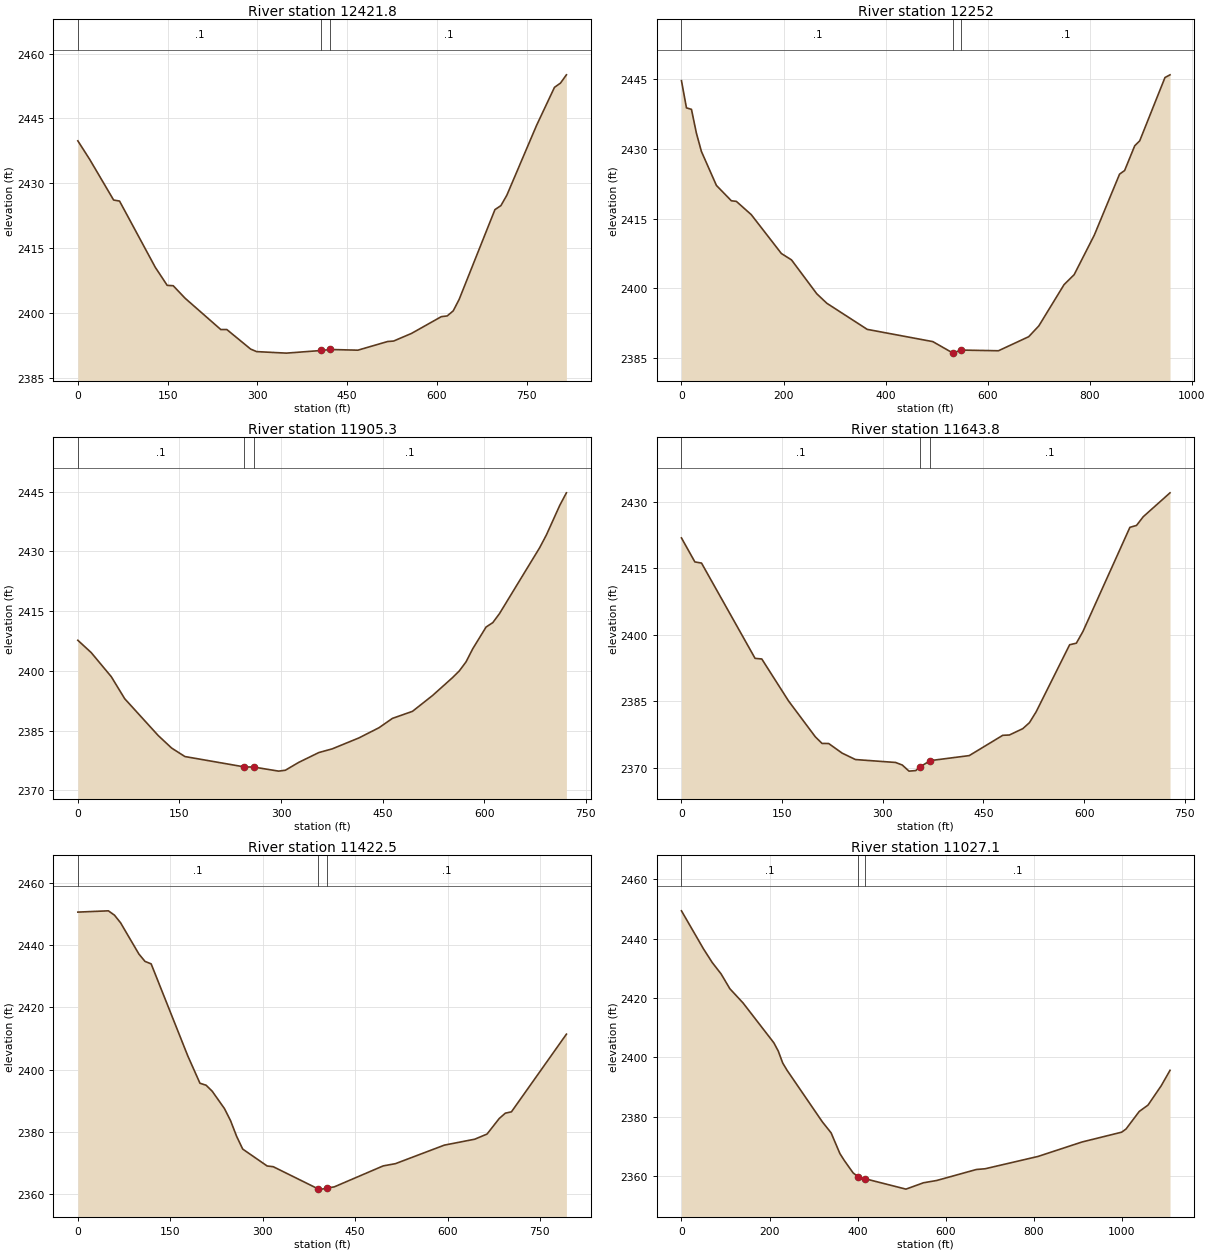
Type RM Length L Ch R = 1 ,12421.8 ,172.7,169.8,166.9
XS GIS Cut Line= 2
     1943439.099       275607.12     1943473.099      276423.128
#Sta/Elev= 30
       0 2439.84    19.9 2435.54    59.8 2426.18    69.7 2425.94   129.5 2410.64
   149.4 2406.48   159.4  2406.4   179.3 2403.51     239 2396.28     249 2396.29
   288.8 2391.78   298.8 2391.19   348.6 2390.84   407.2 2391.45   422.2 2391.68
   468.1 2391.52   517.9 2393.52   527.9 2393.63   557.8 2395.39   607.6 2399.26
   617.5 2399.43   627.5  2400.6   637.4 2403.24   697.2 2423.96   707.2 2424.89
   717.1 2427.28   766.9 2443.44   796.8  2452.2   806.8 2453.17   816.7 2455.08
#Mann= 3 , 0 , 0
       0      .1       0   407.2    .045       0   422.2      .1       0
Bank Sta=407.2,422.2
XS Rating Curve= 0 ,0
Exp/Cntr=0.3,0.1

Type RM Length L Ch R = 1 ,12252   ,358.3,346.6,334.9
XS GIS Cut Line= 3
     1943237.682      275556.693     1943250.575      275722.459
     1943366.611      276505.244
#Sta/Elev= 30
       0 2444.74     9.8 2438.88    19.6 2438.56    29.3 2433.42    39.1 2429.49
    68.5 2422.17    97.8 2418.86   107.6 2418.73   136.9 2415.86   195.9 2407.49
   215.7 2406.12   265.2 2398.82     285 2396.77   364.1 2391.15   492.7 2388.51
   532.3 2386.03   532.4 2386.04   547.4 2386.69   621.3 2386.54   680.6 2389.57
   700.4 2391.89   749.9 2400.79   769.7 2402.94   809.2 2411.46   858.7  2424.6
   868.6 2425.38   888.4 2430.71   898.2 2431.78   947.7 2445.42   957.6    2446
#Mann= 3 , 0 , 0
       0      .1       0   532.4    .045       0   547.4      .1       0
Bank Sta=532.4,547.4
XS Rating Curve= 0 ,0
Exp/Cntr=0.3,0.1

Type RM Length L Ch R = 1 ,11905.3 ,246.4,261.5,276.5
XS GIS Cut Line= 2
     1942832.476       276022.68     1943278.203      276589.969
#Sta/Elev= 30
       0  2407.7    19.8  2404.6    49.4 2398.55    69.2 2393.03   118.6  2383.8
   138.4 2380.65   158.1 2378.51   245.1 2375.93   260.1 2375.86   296.5 2374.85
   306.4 2375.07   326.1 2377.04   355.8 2379.51   375.6 2380.44   415.1 2383.19
   444.7 2385.75   464.5 2388.09   494.1 2389.86   523.8 2393.84   553.4 2398.35
   563.3 2400.02   573.2 2402.28   583.1 2405.57   602.8 2411.03   612.7 2412.13
   622.6  2414.4   681.9 2430.94   691.8 2434.13   711.6 2441.58   721.4 2444.72
#Mann= 3 , 0 , 0
       0      .1       0   245.1    .045       0   260.1      .1       0
Bank Sta=245.1,260.1
XS Rating Curve= 0 ,0
Exp/Cntr=0.3,0.1

Type RM Length L Ch R = 1 ,11643.8 ,213.2,221.3,229.3
XS GIS Cut Line= 2
     1942771.092      276007.124     1942783.092      276735.131
#Sta/Elev= 30
       0  2421.8      20 2416.39    29.9 2416.13   109.7 2394.66   119.7 2394.52
   159.6 2385.06   199.5 2376.98   209.5 2375.49   219.4 2375.47   239.4 2373.31
   259.3 2371.86   319.2  2371.2   329.1 2370.62   339.1 2369.25   349.1 2369.37
   355.9 2370.25   370.9 2371.62   428.9 2372.75   478.8 2377.32   488.7 2377.39
   508.7 2378.82   518.6 2380.17   528.6 2382.62   578.5 2397.73   588.5 2398.08
   598.4 2400.74   668.3 2424.18   678.2 2424.62   688.2 2426.58   728.1 2431.96
#Mann= 3 , 0 , 0
       0      .1       0   355.9    .045       0   370.9      .1       0
Bank Sta=355.9,370.9
XS Rating Curve= 0 ,0
Exp/Cntr=0.3,0.1

Type RM Length L Ch R = 1 ,11422.5 ,387.2,395.1,403
XS GIS Cut Line= 2
     1942705.388      275926.904      1942436.89      276673.077
#Sta/Elev= 30
       0 2450.55    49.6 2450.96    59.5 2449.56    69.4 2447.11    99.1  2437.1
     109 2434.74     119 2433.94   178.4 2404.45   198.2 2395.65   208.2 2395.01
   218.1 2393.09   237.9 2387.54   247.8 2383.68   257.7 2378.63   267.6 2374.53
   307.3  2369.1   317.2 2368.87   389.4 2361.82   396.5 2361.68   404.4 2362.03
   416.3 2362.41   495.6 2369.13   515.5 2369.85   594.8 2375.79   644.3  2377.7
   664.2 2379.35     684 2384.35   693.9 2386.05   703.8 2386.48     793 2411.39
#Mann= 3 , 0 , 0
       0      .1       0   389.4    .045       0   404.4      .1       0
Bank Sta=389.4,404.4
XS Rating Curve= 0 ,0
Exp/Cntr=0.3,0.1

Type RM Length L Ch R = 1 ,11027.1 ,458.3,458.6,459
XS GIS Cut Line= 2
     1942603.618      275689.417      1941889.45      276538.397
#Sta/Elev= 30
       0 2449.33      50 2436.54      70 2431.92      90 2428.11   109.9 2423.13
   139.9 2418.34   209.9 2404.92   219.9 2402.14   229.9 2398.15   239.9 2395.68
   319.8 2378.38   339.8 2374.66   359.8 2367.68   369.8 2365.36   389.8 2361.18
   401.5 2359.87   416.5 2359.24   509.7 2355.73   549.7 2357.87   579.7 2358.64
   669.6 2362.33   689.6 2362.58   809.6 2366.72   909.5 2371.58   999.5 2374.88
  1009.5 2375.95  1039.4 2381.84  1059.4 2383.99  1089.4  2390.5  1109.4 2395.69
#Mann= 3 , 0 , 0
       0      .1       0   401.5    .045       0   416.5      .1       0
Bank Sta=401.5,416.5
XS Rating Curve= 0 ,0
Exp/Cntr=0.3,0.1

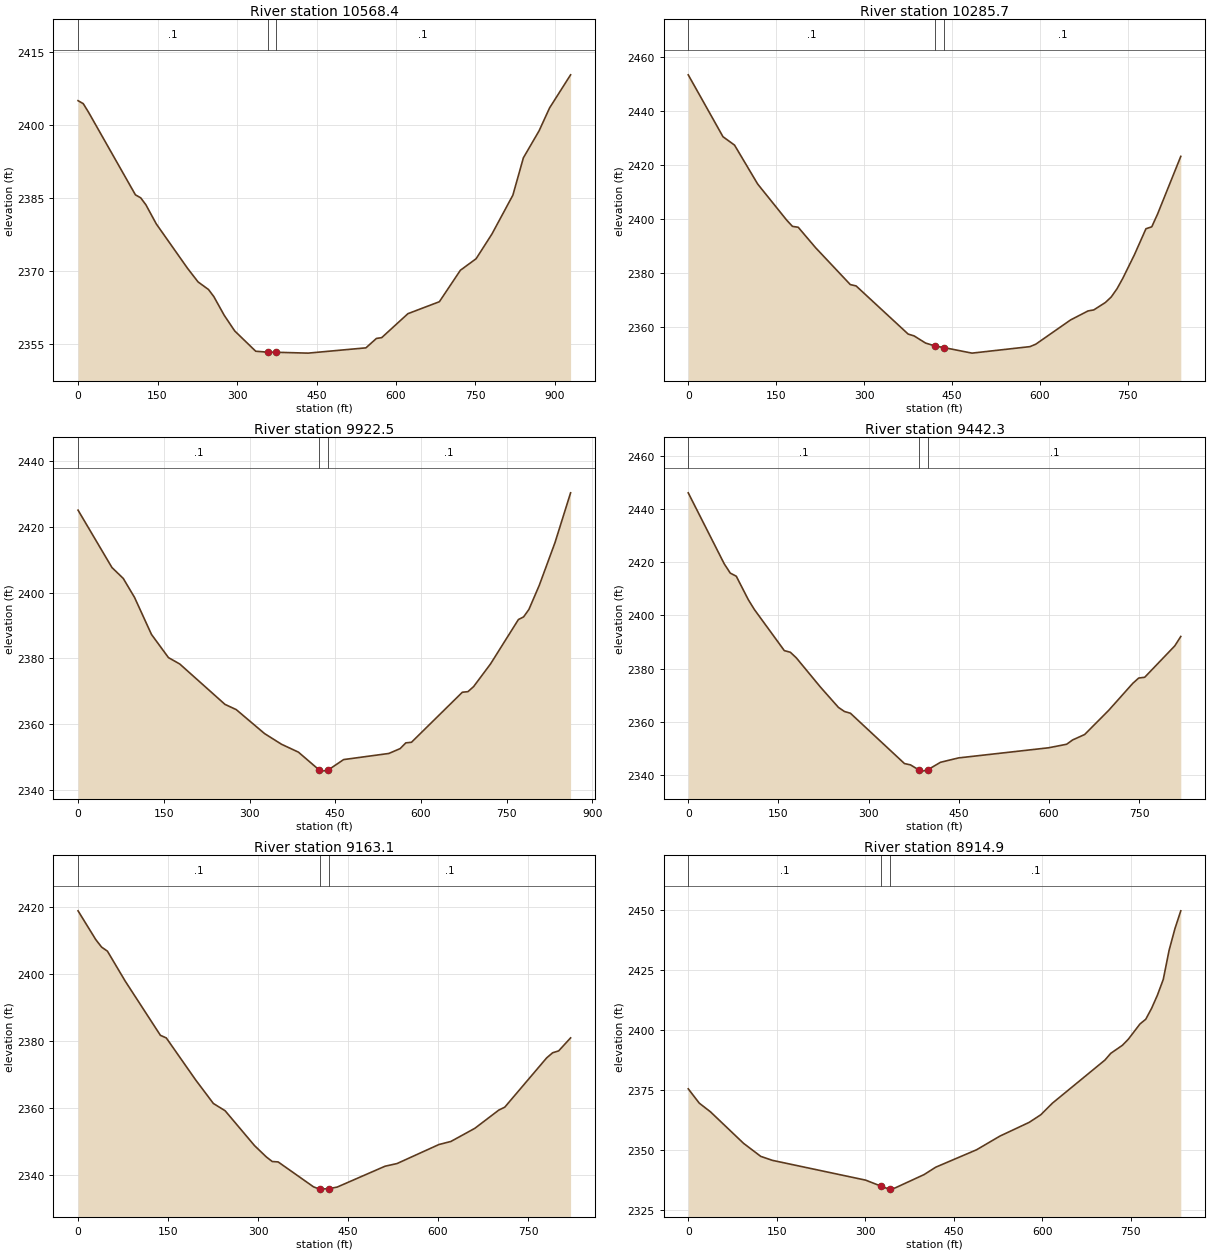
Type RM Length L Ch R = 1 ,10568.4 ,289.3,282.8,276.3
XS GIS Cut Line= 3
     1942206.248      275466.443     1942057.058      275674.571
     1941672.113      276227.125
#Sta/Elev= 30
       0 2405.06     9.8 2404.45    19.7  2402.7   108.3 2385.65   118.2 2385.04
     128 2383.61   147.7 2379.65   206.8 2370.48   226.5  2367.7   246.2 2366.13
   256.1  2364.7   275.9 2360.81   295.7 2357.59   335.3 2353.41   357.7 2353.22
   372.7  2353.2   434.3 2353.02   543.3 2354.11   563.1 2356.05     573 2356.21
   622.5 2361.15   681.9 2363.62   721.5  2370.1   751.2 2372.48     781 2377.56
   820.6 2385.59   840.4 2393.28   870.1 2398.86   889.9 2403.58   929.5 2410.39
#Mann= 3 , 0 , 0
       0      .1       0   357.7    .045       0   372.7      .1       0
Bank Sta=357.7,372.7
XS Rating Curve= 0 ,0
Exp/Cntr=0.3,0.1

Type RM Length L Ch R = 1 ,10285.7 ,362.5,363.1,363.7
XS GIS Cut Line= 3
     1941961.322       275218.04      1941780.23      275580.228
     1941608.756      275980.385
#Sta/Elev= 30
       0 2453.56    59.3 2430.62      79 2427.51   118.5 2413.08   167.9 2399.73
   177.8  2397.4   187.6 2397.08   217.3 2389.49   276.5 2375.83   286.4 2375.33
   375.3 2357.47   385.2 2356.83   404.9 2354.16   421.2 2353.07   436.2 2352.49
   484.1 2350.43     583 2352.84   592.9 2353.74   652.3 2362.73     682 2366.06
   691.9 2366.45   711.7  2369.2   721.6 2371.23   731.4 2374.25   741.3 2378.12
   761.1 2386.84   780.9 2396.53   790.8 2397.24   800.7 2401.97   840.3 2423.34
#Mann= 3 , 0 , 0
       0      .1       0   421.2    .045       0   436.2      .1       0
Bank Sta=421.2,436.2
XS Rating Curve= 0 ,0
Exp/Cntr=0.3,0.1

Type RM Length L Ch R = 1 ,9922.5  ,482.9,480.2,477.3
XS GIS Cut Line= 3
      1941606.62      275126.164     1941285.325      275816.393
      1941241.12      275906.644
#Sta/Elev= 30
       0 2425.03    59.3  2407.6    79.1 2404.28    98.9 2398.49   128.5 2387.25
   158.2 2380.21     178 2378.26   257.1 2365.99   276.8  2364.4   326.3 2357.12
     356 2353.87   385.6 2351.47   421.6  2346.1   425.2  2345.7   436.6 2345.92
   464.7 2349.21   543.8 2351.07   563.6 2352.55   573.5 2354.29   583.4 2354.47
   672.4 2369.68   682.2 2369.86   692.1 2371.39   721.8 2378.31   770.5 2391.78
   779.6 2392.59   788.8 2394.83     807 2402.18   834.4 2415.11   861.8  2430.3
#Mann= 3 , 0 , 0
       0      .1       0   421.6    .045       0   436.6      .1       0
Bank Sta=421.6,436.6
XS Rating Curve= 0 ,0
Exp/Cntr=0.3,0.1

Type RM Length L Ch R = 1 ,9442.3  ,281.1,279.2,275.2
XS GIS Cut Line= 3
     1941120.001      274930.935     1940997.345       275321.62
      1940881.63      275714.513
#Sta/Elev= 30
       0 2446.03    59.9 2419.34    69.9 2415.87    79.9  2414.7    99.9 2405.89
   109.9 2402.22   159.8 2386.75   169.8 2386.14   179.8 2384.02   219.7 2373.09
   249.7 2365.44   259.7 2363.89   269.7 2363.23   359.6 2344.32   369.5 2343.84
   383.4 2341.96   389.5 2341.48   398.4 2341.99   419.5  2344.8   449.4 2346.44
   599.3 2350.25   629.3 2351.58   639.2 2353.19   659.2 2355.23   699.2 2364.31
   739.2 2374.44   749.1 2376.45   759.1 2376.74   809.1 2388.53   819.1 2392.06
#Mann= 3 , 0 , 0
       0      .1       0   383.4    .045       0   398.4      .1       0
Bank Sta=383.4,398.4
XS Rating Curve= 0 ,0
Exp/Cntr=0.3,0.1

Type RM Length L Ch R = 1 ,9163.1  ,231.2,248.1,267
XS GIS Cut Line= 3
      1940817.81      274859.803      1940728.01      275261.843
     1940681.135      275668.217
#Sta/Elev= 30
       0 2418.99    29.4 2410.43    39.2 2408.15      49 2406.92    78.5    2398
   137.3 2381.75   147.1 2380.97   196.2 2368.37   225.6 2361.36   245.2 2359.18
   294.2 2348.75   313.9 2345.36   323.7    2344   333.5 2343.88   392.3 2336.45
   402.1 2335.74   403.4 2335.75   418.4 2335.88   431.9 2336.35   511.7 2342.59
   531.7 2343.39   601.5 2349.08   621.5    2350   661.4 2353.93   701.3 2359.38
   711.3 2360.26   781.1    2375   791.1 2376.53   801.1 2377.09     821 2380.98
#Mann= 3 , 0 , 0
       0      .1       0   403.4    .045       0   418.4      .1       0
Bank Sta=403.4,418.4
XS Rating Curve= 0 ,0
Exp/Cntr=0.3,0.1

Type RM Length L Ch R = 1 ,8914.9  ,270.9,271.8,272.8
XS GIS Cut Line= 3
     1940745.664      274978.353     1940677.515      275055.711
     1940088.431      275489.689
#Sta/Elev= 30
       0 2375.45    18.7 2369.47    37.5  2365.9    93.7 2352.73   122.9 2347.28
   142.6 2345.62   300.8 2337.36   326.9 2334.84   340.4 2333.62   341.9 2333.69
   350.3 2334.08   399.7 2339.68   419.5 2342.77   488.7 2350.03   528.3 2355.74
   577.7 2361.44   597.5 2364.62   617.2 2369.46   706.2 2387.43   716.1 2390.24
   735.9 2393.61   745.8 2396.11   765.6 2402.48   775.4 2404.45   785.3    2409
   795.2  2414.5   805.1 2421.06     815 2433.22   824.9 2442.25   834.8 2449.67
#Mann= 3 , 0 , 0
       0      .1       0   326.9    .045       0   341.9      .1       0
Bank Sta=326.9,341.9
XS Rating Curve= 0 ,0
Exp/Cntr=0.3,0.1

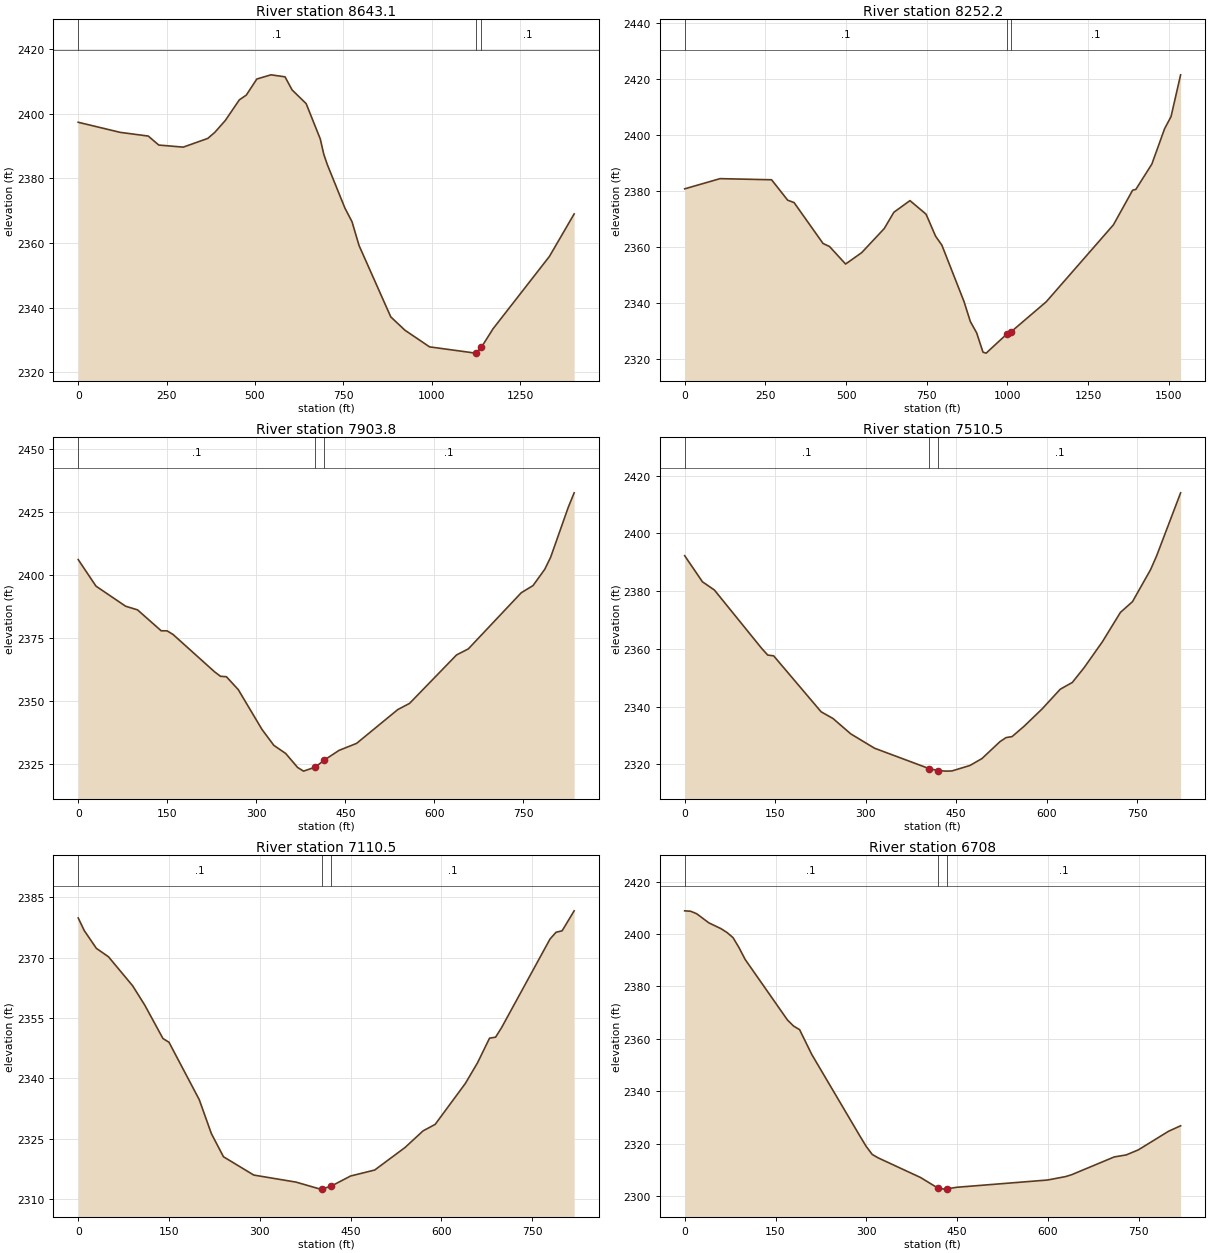
Type RM Length L Ch R = 1 ,8643.1  ,426,390.7,355.4
XS GIS Cut Line= 3
     1940968.527      274184.517     1940824.863      274668.923
     1940067.864      275151.487
#Sta/Elev= 30
       0 2397.41   118.9 2394.28   198.1 2393.14   227.9 2390.35   297.2 2389.71
   366.6 2392.41   386.4 2394.28   416.1 2397.96   455.7 2404.34   475.5 2405.83
   505.3 2410.81   545.2 2412.11   585.1 2411.49     605 2407.44   644.9 2403.18
   684.8 2392.24   694.8 2387.47   704.8 2384.27   754.6  2370.8   774.6 2366.59
   794.5 2359.22   884.3  2337.1   924.2 2332.99     994 2327.82  1123.7 2325.88
  1125.4    2326  1140.4 2327.67  1173.6 2333.43  1333.2 2355.87    1403 2369.01
#Mann= 3 , 0 , 0
       0      .1       0  1125.4    .045       0  1140.4      .1       0
Bank Sta=1125.4,1140.4
XS Rating Curve= 0 ,0
Exp/Cntr=0.3,0.1

Type RM Length L Ch R = 1 ,8252.2  ,343.9,348.4,352.8
XS GIS Cut Line= 4
     1940314.672      273983.756     1939868.995      274584.564
     1940062.339      274902.837     1939980.304      275311.127
#Sta/Elev= 30
       0 2380.84   109.7 2384.48   269.3 2384.08   319.2  2376.8   339.1 2375.93
   428.9 2361.34   448.8 2360.28   498.7 2354.02   548.6 2358.09   618.4 2366.67
   648.3 2372.49   698.2 2376.64   748.1  2371.8   777.5 2363.96   797.1 2360.75
   865.7 2340.63   885.3  2333.5   904.9 2329.46   924.5 2322.57   934.3 2322.24
   997.4 2328.95  1012.4 2329.93  1120.5 2340.56  1328.7 2368.01  1388.2 2380.36
  1398.1 2380.64  1447.7 2389.66  1487.3  2402.3  1507.2 2406.62  1536.9 2421.51
#Mann= 3 , 0 , 0
       0      .1       0   997.4    .045       0  1012.4      .1       0
Bank Sta=997.4,1012.4
XS Rating Curve= 0 ,0
Exp/Cntr=0.3,0.1

Type RM Length L Ch R = 1 ,7903.8  ,378.1,393,410.6
XS GIS Cut Line= 3
     1939546.978      274572.632     1939699.154      274974.257
     1939866.765      275344.181
#Sta/Elev= 30
       0 2406.12      30 2395.57    79.9  2387.6    99.9 2386.16   139.8 2377.85
   149.8 2377.82   159.8 2376.38   229.7 2361.56   239.7 2359.77   249.7  2359.6
   269.7 2354.47   309.6 2338.68   329.6 2332.34   349.6 2329.11   369.6 2323.57
   379.6  2322.1   399.3 2323.67   414.3 2326.43   439.4 2330.34   469.1 2333.13
   538.4 2346.54   558.3 2349.01   637.5 2368.26   657.3 2370.65   746.5 2392.96
   766.3  2395.8   786.1 2402.28     796 2407.06   825.7 2426.91   835.6 2432.64
#Mann= 3 , 0 , 0
       0      .1       0   399.3    .045       0   414.3      .1       0
Bank Sta=399.3,414.3
XS Rating Curve= 0 ,0
Exp/Cntr=0.3,0.1

Type RM Length L Ch R = 1 ,7510.5  ,394.7,400,403.4
XS GIS Cut Line= 3
     1939431.589      274573.542     1939309.803      274968.245
     1939144.926      275342.684
#Sta/Elev= 30
       0 2392.24    29.5  2383.2    49.2 2380.38   127.8 2360.12   137.7 2357.84
   147.5 2357.58   226.2  2338.2   245.9 2335.88   275.4 2330.55   314.7  2325.6
   405.6 2318.51   420.6 2317.85     433 2317.66     443 2317.72   472.9 2319.61
   492.9 2322.02   522.8 2327.88   532.8 2329.27   542.8 2329.62   562.8 2333.21
   592.7 2339.22   622.6 2346.01   642.6 2348.35   662.5 2353.56   692.5 2362.44
   722.4 2372.61   742.4 2376.33   772.3 2387.38   782.3 2392.12   822.2 2414.01
#Mann= 3 , 0 , 0
       0      .1       0   405.6    .045       0   420.6      .1       0
Bank Sta=405.6,420.6
XS Rating Curve= 0 ,0
Exp/Cntr=0.3,0.1

Type RM Length L Ch R = 1 ,7110.5  ,396.3,402.5,407.9
XS GIS Cut Line= 3
     1939143.717      274485.533     1938934.332      274838.088
      1938714.22      275183.287
#Sta/Elev= 30
       0 2379.91      10 2376.77      30 2372.35      50 2370.26      90 2363.03
     110 2358.23     140 2349.94     150    2349     200 2334.73     220  2326.3
     240 2320.54     290 2315.99     360 2314.23     400 2312.49   402.5 2312.52
   417.5  2313.2     450 2315.75   489.9 2317.24   539.9 2322.83   569.8 2326.98
   589.8 2328.59   639.7 2338.78   659.7 2343.88   679.6 2350.02   689.6 2350.27
   699.6 2352.67   779.5 2374.66   789.5 2376.36   799.5 2376.71   819.4 2381.68
#Mann= 3 , 0 , 0
       0      .1       0   402.5    .045       0   417.5      .1       0
Bank Sta=402.5,417.5
XS Rating Curve= 0 ,0
Exp/Cntr=0.3,0.1

Type RM Length L Ch R = 1 ,6708    ,397.3,404.8,412.3
XS GIS Cut Line= 3
       1938931.8      274294.836     1938633.686      274575.648
     1938338.005      274858.914
#Sta/Elev= 30
       0 2408.89      10 2408.73      20 2407.75      40 2404.29    59.9 2402.09
    69.9 2400.62    79.9 2398.65    89.9 2394.77    99.9 2390.32   169.8 2367.19
   179.8  2364.9   189.8 2363.51   209.8 2354.08   289.7 2322.78   299.7 2318.96
   309.7 2315.87   319.6 2314.55   389.6 2307.05     418 2303.04   429.5 2302.62
     433 2302.74   449.5 2303.33   599.3  2306.1   629.3 2307.42   639.2 2308.14
   709.2  2314.9   729.1 2315.68   749.1  2317.6     799 2324.71     819 2326.81
#Mann= 3 , 0 , 0
       0      .1       0     418    .045       0     433      .1       0
Bank Sta=418,433
XS Rating Curve= 0 ,0
Exp/Cntr=0.3,0.1