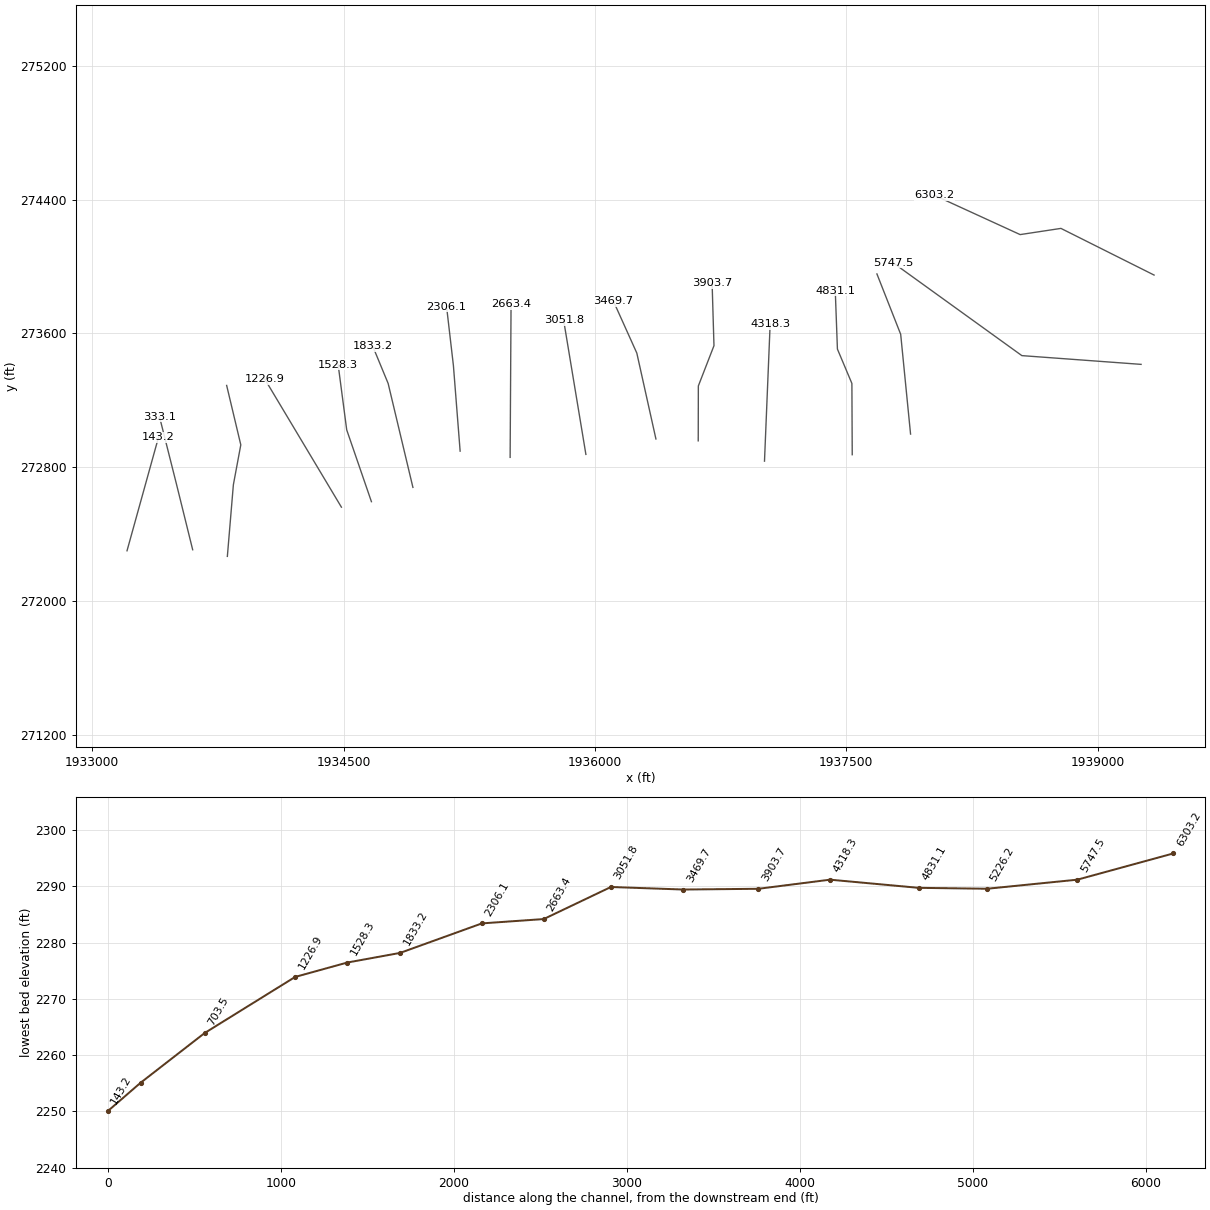
HEC-RAS study LttlBvrCrk.prj: LttlBvrCrk

--- LttlBvrCrk.g01 (geometry) --- (continued)

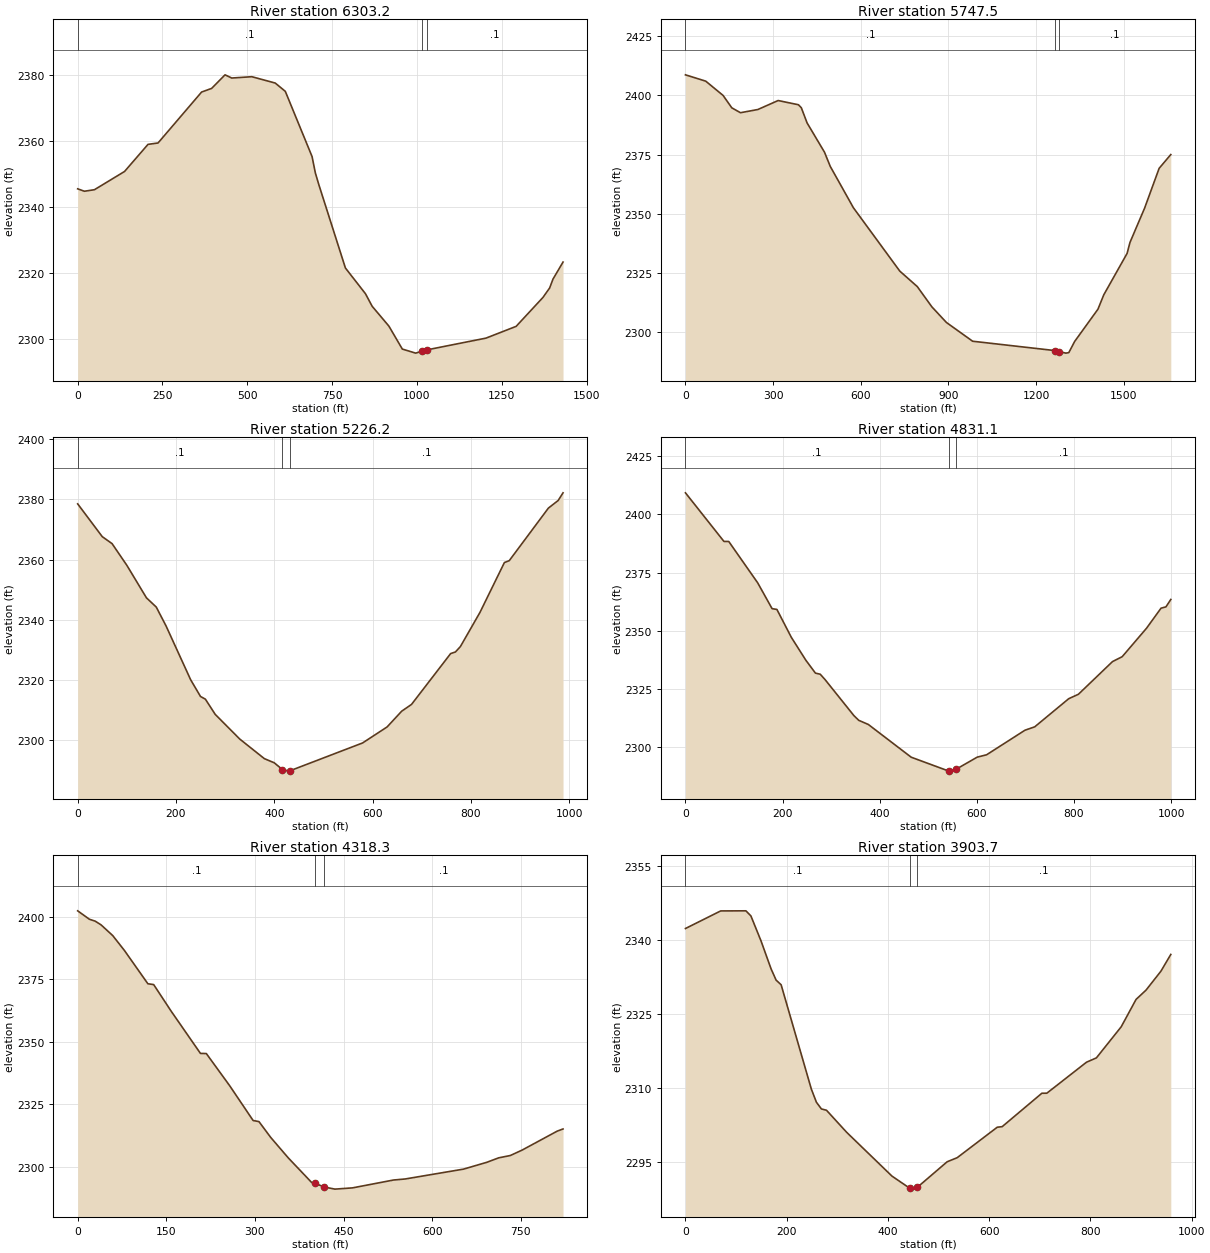
Type RM Length L Ch R = 1 ,6303.2  ,559.7,555.3,551
XS GIS Cut Line= 4
     1939336.651      273948.761     1938780.831      274227.823
     1938537.474      274190.772     1938026.129       274425.57
#Sta/Elev= 30
       0 2345.57    19.7 2344.84    49.4  2345.3   138.2 2350.82   207.3 2359.02
   236.9 2359.44   365.3 2374.85   394.9 2375.95   434.4 2380.06   454.1 2379.09
   513.4 2379.49   582.4 2377.57   612.1 2375.06   690.9 2355.35   700.7 2350.37
   710.6 2346.93   789.3 2321.61   848.4 2313.83   868.1 2310.04   917.5 2304.03
     957 2297.09   996.4 2295.86  1013.7  2296.4  1028.7 2296.83  1203.7  2300.4
  1292.6 2303.96  1371.6 2312.71  1391.3 2315.57  1401.2 2318.26  1430.8 2323.41
#Mann= 3 , 0 , 0
       0      .1       0  1013.7    .045       0  1028.7      .1       0
Bank Sta=1013.7,1028.7
XS Rating Curve= 0 ,0
Exp/Cntr=0.3,0.1

Type RM Length L Ch R = 1 ,5747.5  ,540.2,521,501.9
XS GIS Cut Line= 3
     1939259.294      273414.625     1938547.574      273466.977
     1937779.645      274021.867
#Sta/Elev= 30
       0 2408.65    69.4 2405.98   128.8 2399.95   158.6 2394.72   188.3 2392.66
   247.8 2394.01   317.2  2397.8   386.6 2396.02   396.5 2394.77   416.3 2388.35
   475.8 2376.01   495.6    2370   574.9 2352.53   733.6  2325.8   793.4 2319.28
   843.3 2310.73   893.2 2304.12   982.9 2296.21  1264.9 2292.26  1279.9  2291.8
    1302 2291.19    1312 2291.39    1332 2296.11  1411.8 2309.74  1431.7  2315.8
  1511.5 2333.28  1521.4 2337.92  1571.3 2352.35  1621.2 2369.19  1661.1    2375
#Mann= 3 , 0 , 0
       0      .1       0  1264.9    .045       0  1279.9      .1       0
Bank Sta=1264.9,1279.9
XS Rating Curve= 0 ,0
Exp/Cntr=0.3,0.1

Type RM Length L Ch R = 1 ,5226.2  ,389.3,395.4,401.4
XS GIS Cut Line= 3
     1937883.434      272997.754     1937824.495      273594.512
     1937682.673      273955.514
#Sta/Elev= 30
       0 2378.54      50 2367.63      70  2365.3    99.9 2358.13   139.9 2347.27
   159.9 2344.19   179.9 2337.88   229.9 2319.98   249.9 2314.43   259.8 2313.54
   279.8 2308.48   329.8 2300.25   379.8 2293.74   399.8 2292.37   416.5 2290.11
   429.8 2289.58   431.5 2289.67   579.7 2298.96   629.5 2304.28   659.3 2309.54
   679.2 2311.78   758.8  2328.7   768.7 2329.26   778.7 2331.05   818.5 2342.42
   868.2 2359.01   878.1 2359.64   957.7 2377.13   977.6 2379.67   987.5 2382.22
#Mann= 3 , 0 , 0
       0      .1       0   416.5    .045       0   431.5      .1       0
Bank Sta=416.5,431.5
XS Rating Curve= 0 ,0
Exp/Cntr=0.3,0.1

Type RM Length L Ch R = 1 ,4831.1  ,521.9,512.4,502.9
XS GIS Cut Line= 4
     1937535.325       272874.35     1937533.286      273300.508
     1937446.916      273506.104     1937434.024      273856.055
#Sta/Elev= 30
       0 2409.25    79.3 2388.37    89.2 2388.35   148.7 2370.61   178.4  2359.5
   188.3 2359.18     218  2347.2   247.8  2337.4   267.6 2331.83   277.5 2331.36
   287.4 2329.06   346.9 2313.57   356.8 2311.56   376.6 2309.77   464.9 2295.71
   542.1 2289.77   542.5 2289.74   557.1 2290.52   600.7 2295.74   620.1 2296.76
   699.2 2307.32   719.2 2308.76   789.2 2320.84   809.2 2322.75   879.3 2336.77
   899.3 2338.88   949.3 2351.07   979.3 2359.71   989.4 2360.28   999.4 2363.46
#Mann= 3 , 0 , 0
       0      .1       0   542.1    .045       0   557.1      .1       0
Bank Sta=542.1,557.1
XS Rating Curve= 0 ,0
Exp/Cntr=0.3,0.1

Type RM Length L Ch R = 1 ,4318.3  ,421.9,414.5,407.1
XS GIS Cut Line= 2
     1937011.687      272835.783     1937045.455      273656.448
#Sta/Elev= 30
       0 2402.31    19.8 2398.95    29.7 2398.18    39.6  2396.7    59.4 2392.41
    79.2 2386.45   118.8 2373.19   128.6 2372.86   158.3 2362.21   207.8 2345.37
   217.7 2345.33   257.3 2332.46   296.9 2318.59   306.8 2318.15   326.6 2311.86
   356.2 2303.72   395.8 2293.88     402  2293.5     417 2292.05   435.4 2291.19
   465.1 2291.69   534.4 2294.82   554.2 2295.24   653.1 2299.18   692.7 2301.92
   712.5 2303.68   732.3 2304.62   752.1 2306.77   811.5 2314.34   821.4 2315.21
#Mann= 3 , 0 , 0
       0      .1       0     402    .045       0     417      .1       0
Bank Sta=402,417
XS Rating Curve= 0 ,0
Exp/Cntr=0.3,0.1

Type RM Length L Ch R = 1 ,3903.7  ,421,433.7,446.5
XS GIS Cut Line= 4
     1936616.244      272957.234     1936616.925      273285.532
     1936710.178      273526.364     1936699.127      273898.417
#Sta/Elev= 30
       0 2342.33    69.6 2345.89   119.4 2345.91   129.3 2344.88   149.2 2339.84
   169.1 2334.17   179.1 2331.88     189 2330.94   248.7 2309.82   258.7 2307.16
   268.6  2305.8   278.6 2305.54   318.4 2301.08   407.8 2292.22   443.1 2289.75
   447.5 2289.57   458.1 2289.94     517 2295.11   536.9 2295.94   615.9  2302.1
   625.7 2302.22   704.1 2308.98   713.9 2308.99   792.2 2315.26   811.8 2316.14
   860.8 2322.43   890.2 2327.98   909.8 2329.85   939.2 2333.68   958.8 2337.08
#Mann= 3 , 0 , 0
       0      .1       0   443.1    .045       0   458.1      .1       0
Bank Sta=443.1,458.1
XS Rating Curve= 0 ,0
Exp/Cntr=0.3,0.1

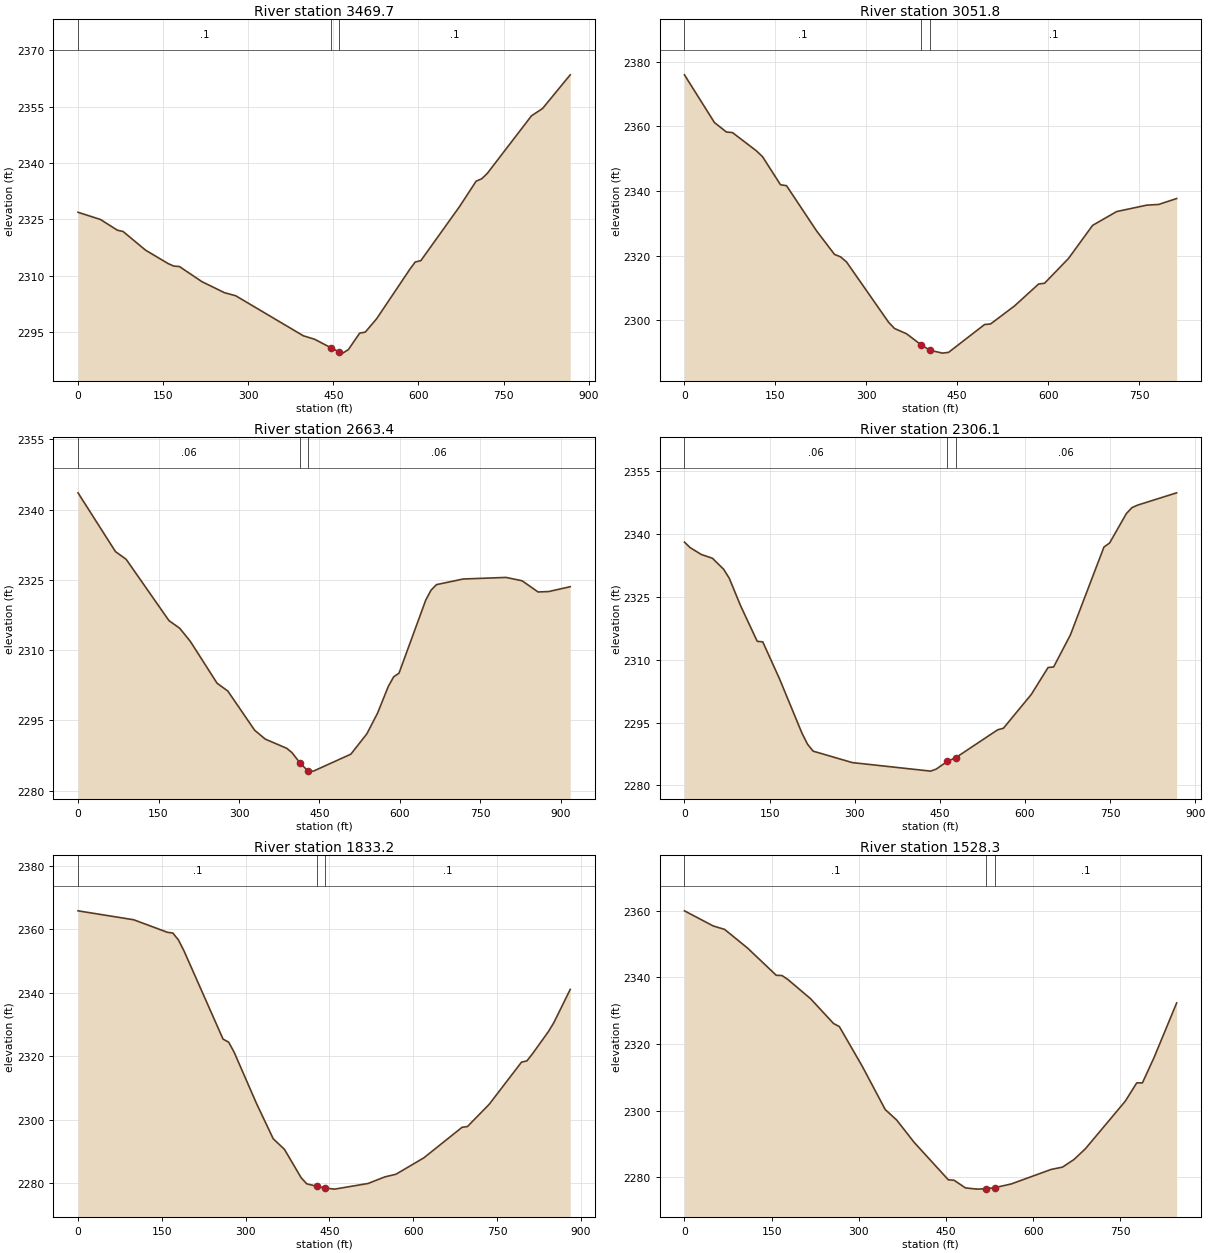
Type RM Length L Ch R = 1 ,3469.7  ,418.9,417.9,417
XS GIS Cut Line= 3
     1936363.735      272968.481     1936249.716       273482.16
     1936109.736      273793.432
#Sta/Elev= 30
       0 2326.89    39.7 2324.96    69.5 2322.11    79.4 2321.78   119.1 2316.81
   158.8 2313.25   168.8 2312.58   178.7 2312.46   218.4 2308.44   258.1 2305.51
     278 2304.69   397.1 2294.05     417 2293.13   445.6 2290.88   460.6 2289.72
   466.6 2289.44   476.5 2290.38   496.4 2294.75   506.3 2295.03   526.2 2298.56
   584.7  2311.7   594.4 2313.68   604.2 2314.02   672.4  2328.4   701.7 2335.16
   711.5 2335.79   721.2 2337.19   799.2 2352.53   818.7 2354.47   867.5 2363.43
#Mann= 3 , 0 , 0
       0      .1       0   445.6    .045       0   460.6      .1       0
Bank Sta=445.6,460.6
XS Rating Curve= 0 ,0
Exp/Cntr=0.3,0.1

Type RM Length L Ch R = 1 ,3051.8  ,392.1,388.3,384.6
XS GIS Cut Line= 2
     1935945.812      272876.192     1935813.199      273677.396
#Sta/Elev= 30
       0 2375.96    49.5  2361.2    69.3 2358.27    79.2  2358.1   118.8 2352.44
   128.8 2350.65   158.5 2341.96   168.4 2341.68   217.9 2327.72   247.6 2320.42
   257.5 2319.67   267.4 2318.09   336.7 2299.47   346.6 2297.51   366.4 2295.88
     390 2292.53     405 2290.77   425.9 2289.89   435.8 2290.13   495.2 2298.74
   505.1 2298.91   544.7  2304.5   584.3 2311.26   594.2 2311.51   633.8  2319.2
   673.4  2329.4   713.1 2333.67   762.6 2335.65   782.4 2335.87   812.1  2337.7
#Mann= 3 , 0 , 0
       0      .1       0     390    .045       0     405      .1       0
Bank Sta=390,405
XS Rating Curve= 0 ,0
Exp/Cntr=0.3,0.1

Type RM Length L Ch R = 1 ,2663.4  ,355.2,357.1,359.1
XS GIS Cut Line= 2
     1935493.638      272858.464     1935499.164      273775.704
#Sta/Elev= 30
       0 2343.57    69.8 2331.03    89.7 2329.39   169.5  2316.3   189.4 2314.69
   209.4 2311.86   259.2 2302.94   279.2 2301.28     329 2292.94     349 2291.02
   388.8 2289.07   398.8 2288.14   413.9 2285.91   428.9  2284.2   438.7 2284.19
   508.5 2287.81   538.4 2292.17   558.3 2296.58   578.3 2302.27   588.2  2304.3
   598.2 2305.09   648.1 2320.69     658 2322.81     668 2323.98   717.8 2325.18
   797.6 2325.52   827.5 2324.81   857.4 2322.42   877.4 2322.51   917.3 2323.54
#Mann= 3 , 0 , 0
       0     .06       0   413.9    .045       0   428.9     .06       0
Bank Sta=413.9,428.9
XS Rating Curve= 0 ,0
Exp/Cntr=0.3,0.1

Type RM Length L Ch R = 1 ,2306.1  ,470.8,472.9,474.9
XS GIS Cut Line= 3
     1935195.259      272895.762     1935155.199      273406.874
      1935114.41      273759.282
#Sta/Elev= 30
       0 2338.11     9.9 2336.82    29.6 2335.17    49.3 2334.26      69 2331.64
    78.9 2329.51    98.6 2323.02   128.2 2314.43     138 2314.29   167.6 2305.44
     207 2292.51   216.9 2289.85   226.8 2288.19   295.8 2285.46   433.8 2283.42
   443.7 2283.91   463.2 2285.73   478.2 2286.64   552.1  2293.3     562 2293.65
   611.2 2301.73   640.8 2308.17   650.6  2308.3   680.2 2315.97   739.3 2336.95
   749.2  2337.9   778.8 2344.93   788.6 2346.35   798.5 2346.95   867.4 2349.89
#Mann= 3 , 0 , 0
       0     .06       0   463.2    .045       0   478.2     .06       0
Bank Sta=463.2,478.2
XS Rating Curve= 0 ,0
Exp/Cntr=0.3,0.1

Type RM Length L Ch R = 1 ,1833.2  ,307.6,305.1,302.5
XS GIS Cut Line= 3
     1934913.456      272678.884     1934765.648      273300.508
     1934673.291      273524.213
#Sta/Elev= 30
       0 2365.87    99.8 2363.05   159.7 2359.12   169.7 2358.86   179.7 2356.71
   189.7 2353.25   259.6 2325.44   269.6 2324.49   279.5  2321.3   319.5 2305.14
   349.4 2294.04   369.4 2290.73   399.4 2281.77   409.3 2279.85     427 2279.08
     442 2278.51   459.2 2278.17   519.2 2279.95   549.1 2282.02   569.1 2282.86
     619 2288.03   687.4 2297.65     697 2297.89   735.8 2304.86   793.8 2318.18
   803.5 2318.59   813.2 2320.76   842.2 2327.87   851.9  2330.7     881  2341.1
#Mann= 3 , 0 , 0
       0      .1       0     427    .045       0     442      .1       0
Bank Sta=427,442
XS Rating Curve= 0 ,0
Exp/Cntr=0.3,0.1

Type RM Length L Ch R = 1 ,1528.3  ,292.2,301.1,310.1
XS GIS Cut Line= 3
     1934665.858      272593.413      1934518.38      273022.849
     1934467.269        273412.4
#Sta/Elev= 30
       0 2359.92    49.4 2355.39    69.1 2354.35   108.6 2348.75   157.9 2340.59
   167.8 2340.51   177.7 2339.36   217.2 2333.53   256.6 2326.12   266.5 2325.21
     306 2313.29   345.5 2300.32   365.2 2297.18   394.8 2290.57     454 2279.26
   463.9 2279.12   483.5 2276.83   503.2 2276.46   519.1 2276.58   534.1 2276.91
   562.1    2278   630.8 2282.36   650.5 2283.06   670.1 2285.32   689.8 2288.55
   758.5 2302.83   778.2 2308.32     788 2308.33   807.7 2315.79   846.9 2332.29
#Mann= 3 , 0 , 0
       0      .1       0   519.1    .045       0   534.1      .1       0
Bank Sta=519.1,534.1
XS Rating Curve= 0 ,0
Exp/Cntr=0.3,0.1

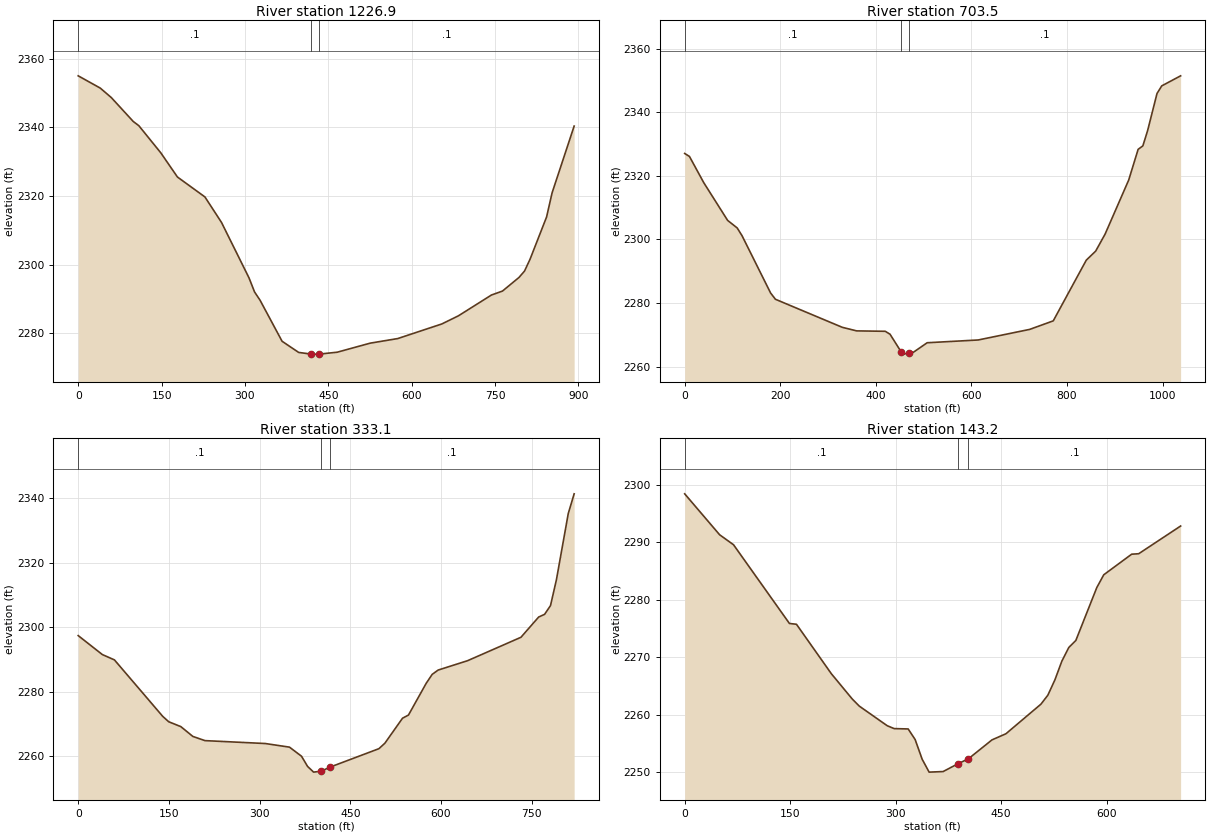
Type RM Length L Ch R = 1 ,1226.9  ,539.5,523.4,507.4
XS GIS Cut Line= 2
     1934486.753      272560.618      1934029.37      273326.754
#Sta/Elev= 30
       0 2355.03    39.7 2351.45    59.5  2348.7    99.1 2341.71   109.1 2340.49
   148.7 2332.56   178.5 2325.54     228 2319.72   257.8  2312.3   307.3 2296.13
   317.3 2292.02   327.2 2289.61   366.8 2277.65   396.6  2274.4   418.3 2273.92
   426.3  2273.9   433.3  2273.9     466 2274.46   525.4  2277.1     575 2278.44
   654.3  2282.7   684.1 2285.07   743.6 2291.14   763.4 2292.29   793.1 2296.26
     803 2298.11     813 2301.58   842.7 2313.88   852.6 2320.91   892.3 2340.38
#Mann= 3 , 0 , 0
       0      .1       0   418.3    .045       0   433.3      .1       0
Bank Sta=418.3,433.3
XS Rating Curve= 0 ,0
Exp/Cntr=0.3,0.1

Type RM Length L Ch R = 1 ,703.5   ,360.4,370.1,379.7
XS GIS Cut Line= 4
     1933806.046      272266.311     1933841.962       272694.54
     1933886.251      272933.248     1933801.902      273288.536
#Sta/Elev= 30
       0 2327.02      10 2326.09      40 2317.82    89.9 2305.97   109.9  2303.6
   119.9 2301.19   179.9 2283.12   189.9 2281.17   329.8 2272.35   359.8 2271.23
   419.7  2271.1   429.7 2270.18   453.5  2264.5   458.9 2263.92   468.5 2264.36
   478.3 2264.48   507.4  2267.5   614.2 2268.37   721.9  2271.7   771.2 2274.38
   840.3 2293.47     860 2296.32   879.8  2301.7   929.1 2318.68   948.8 2328.32
   958.7 2329.41   968.6 2334.19   988.3 2345.88   998.2 2348.28  1037.7 2351.44
#Mann= 3 , 0 , 0
       0      .1       0   453.5    .045       0   468.5      .1       0
Bank Sta=453.5,468.5
XS Rating Curve= 0 ,0
Exp/Cntr=0.3,0.1

Type RM Length L Ch R = 1 ,333.1   ,201.6,189.9,178
XS GIS Cut Line= 3
     1933599.127      272305.877     1933501.156      272703.209
     1933400.939      273101.819
#Sta/Elev= 30
       0 2297.37    39.9  2291.5    59.9 2289.85   139.7 2272.37   149.7 2270.68
   169.7 2269.18   189.6 2266.14   209.6 2264.84   309.4 2263.94   349.4 2262.82
   369.3 2260.01   379.3 2256.86   389.3 2255.08   401.7 2255.37   416.7 2256.65
   497.3 2262.34   507.1 2264.02   536.4 2271.79   546.2 2272.76   575.6 2282.62
   585.4 2285.36   595.2 2286.69   644.1 2289.61   732.2 2296.85   761.5 2303.12
   771.3 2303.96   781.1 2306.67   790.9  2314.7   810.5 2335.22   820.2 2341.29
#Mann= 3 , 0 , 0
       0      .1       0   401.7    .045       0   416.7      .1       0
Bank Sta=401.7,416.7
XS Rating Curve= 0 ,0
Exp/Cntr=0.3,0.1

Type RM Length L Ch R = 1 ,143.2   ,137.9,143.2,148.5
XS GIS Cut Line= 2
     1933207.239        272299.8     1933395.465      272979.605
#Sta/Elev= 30
       0 2298.44    49.7 2291.32    69.5 2289.58     149 2275.89     159 2275.75
   208.6 2267.15   238.4 2262.74   248.4 2261.51   288.1  2258.1     298  2257.6
   317.9 2257.54   327.8  2255.7   337.8 2252.27   347.7 2250.03   367.6 2250.13
   388.6 2251.48   403.6 2252.35   437.1 2255.64     457 2256.71   506.7 2261.85
   516.6 2263.42   526.6 2266.08   536.5 2269.34   546.4 2271.72   556.4 2272.94
   586.2 2282.14   596.1 2284.36   635.8 2287.94   645.8 2288.02   705.4 2292.84
#Mann= 3 , 0 , 0
       0      .1       0   388.6    .045       0   403.6      .1       0
Bank Sta=388.6,403.6
XS Rating Curve= 0 ,0
Exp/Cntr=0.3,0.1

Chan Stop Cuts=-1
Use User Specified Reach Order=0
Composite Channel Slope=5